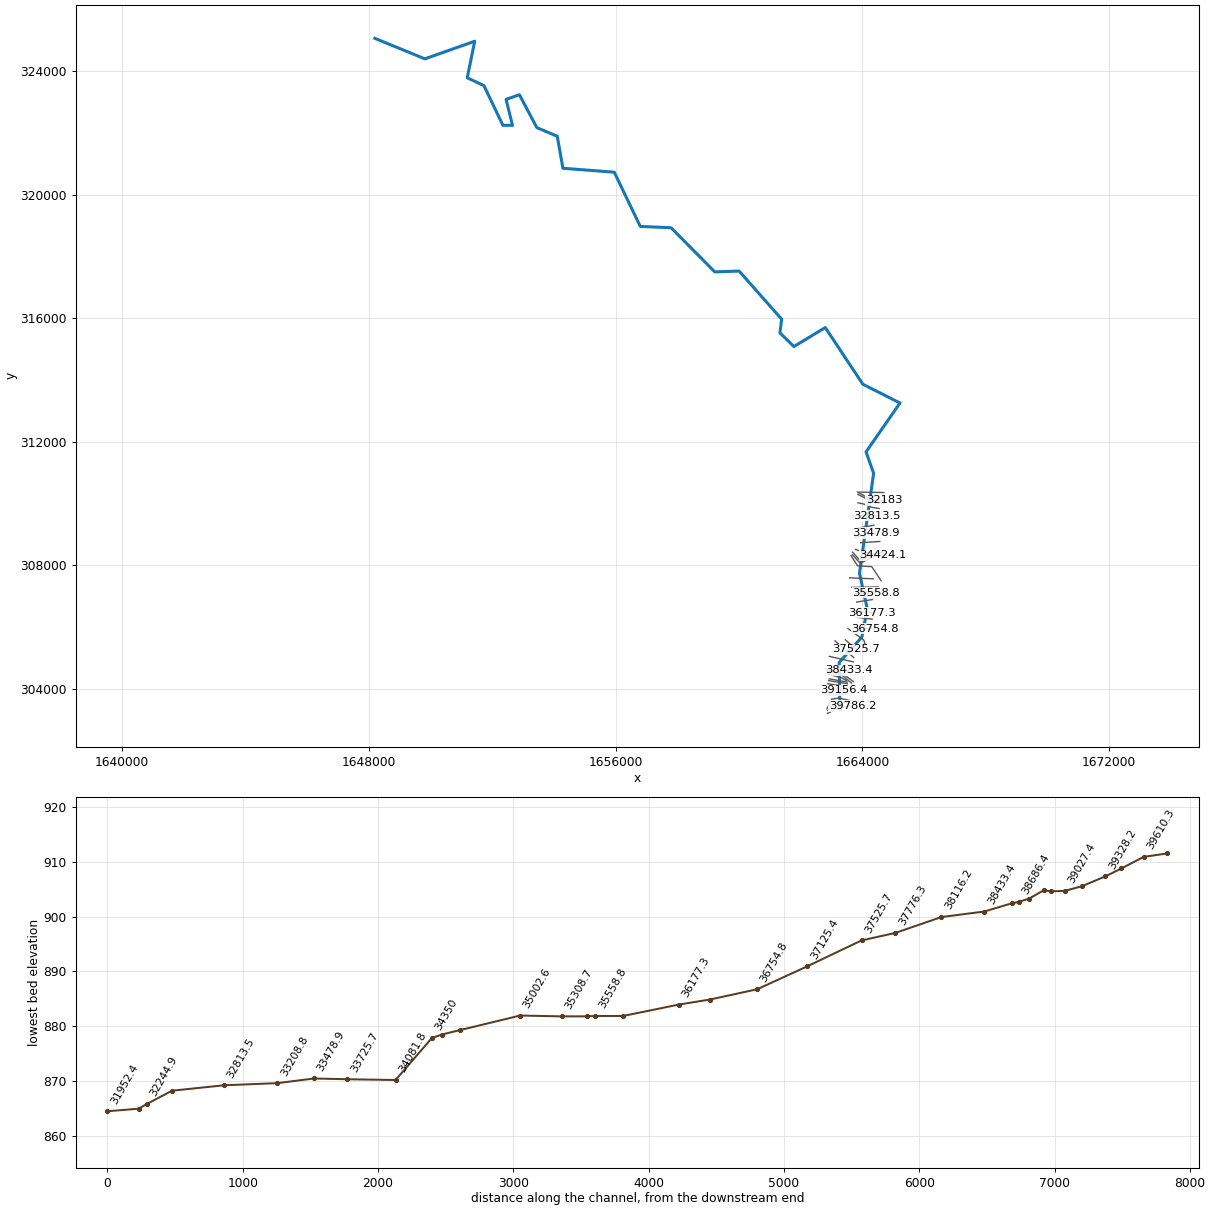
--- RBNSONFRK.prj (project) ---

Proj Title=RBNSONFRK
Current Plan=p01
Geom File=g01
Flow File=f01
Plan File=p01
DSS Export Rating Curves=0
DSS Export Rating Curve Sorted=0
DSS Export Volume Flow Curves=0
DXF OffsetX=0
DXF OffsetY=0
DXF ScaleX=0
DXF ScaleY=0

--- RBNSONFRK.p01 (plan) ---

Plan Title=Floodplain
Program Version=4.00
Geom File=g01
Flow File=f01
K Sum by GR=0
Std Step Tol=0.01
Critical Tol=0.01
Num of Std Step Trials=20
Max Error Tol=0.3
Flow Tol Ratio=0.001
Split Flow NTrial=30
Split Flow Tol=0.02
Split Flow Ratio=0.02
Log Output Level=0
Friction Slope Method=1
Unsteady Friction Slope Method=2
Unsteady Bridges Friction Slope Method=1
Global Log Level=0
CheckData=False
Run HTab=0
Run UNet=0
Run PostProcess=0
UNET Theta=0
UNET Theta Warmup=0
UNET ZTol=0
UNET ZSATol=0
UNET MxIter=0
UNET MaxInSteps=0
UNET DtIC=0
UNET DtMin=0
UNET MaxCRTS=0
UNET WFStab=0
UNET SFStab=0
UNET WFX=0
UNET SFX=0
UNET DSS MLevel=0
UNET DZMax Abort=0
UNET Convert EG Bridges=0
UNET Use Existing IB Tables=0
UNET Froude Limit=0
UNET Froude Power=0
Write IC File=0
Echo Input=False
Echo Output=False
Write Detailed=0

--- RBNSONFRK.f01 (steady flow) ---

Flow Title=NFF Regression Equation
Program Version=4.10
Number of Profiles= 1
Profile Names=P100yr
River Rch & RM=RBNSONFRK,Main            ,39786.2
764.6481
River Rch & RM=RBNSONFRK,Main            ,39156.4
769.5648
River Rch & RM=RBNSONFRK,Main            ,38926.7
953.6702
River Rch & RM=RBNSONFRK,Main            ,37125.4
1028.214
River Rch & RM=RBNSONFRK,Main            ,36754.8
 1232.99
River Rch & RM=RBNSONFRK,Main            ,34558.5
1258.269
River Rch & RM=RBNSONFRK,Main            ,34424.1
 1509.03
River Rch & RM=RBNSONFRK,Main            ,33725.7
1604.571
River Rch & RM=RBNSONFRK,Main            ,28321.3
1773.179
River Rch & RM=RBNSONFRK,Main            ,27751.5
2036.783
River Rch & RM=RBNSONFRK,Main            ,26014.9
2076.798
River Rch & RM=RBNSONFRK,Main            ,25486.5
2716.612
River Rch & RM=RBNSONFRK,Main            ,22255.3
2823.084
River Rch & RM=RBNSONFRK,Main            ,16309
3122.387
River Rch & RM=RBNSONFRK,Main            ,998.5
3406.275
River Rch & RM=RBNSONFRK,Main            ,645.7
 4337.81
River Rch & RM=RBNSONFRK,Main            ,120.6
4340.662
Boundary for River Rch & Prof#=RBNSONFRK,Main            , 1
Up Type= 0
Dn Type= 1
Dn Known WS=792
DSS Import GetInterval= 0
DSS Import GetPeak= 0
DSS Import FillOption= 0

--- RBNSONFRK.g01 (geometry) ---

Geom Title=USGS 10m DEM
Program Version=4.10

River Reach=RBNSONFRK       ,Main
Reach XY= 30
     1663275.002      303330.977     1663250.029      304854.876
     1663984.751      305675.015     1664161.748      306587.884
     1663908.102      307741.009     1664366.371      310977.967
     1664122.063      311670.836     1665220.538      313253.487
     1664016.024      313861.604     1662799.774      315695.367
     1661782.413      315080.783     1661329.288      315522.624
     1661384.843        315966.2     1660006.371      317523.492
     1659216.614      317497.971     1657798.327      318926.096
      1656800.41      318969.846     1655956.308      320724.837
     1654291.911      320851.857     1654108.827      321888.163
     1653446.573      322167.607     1652880.841      323231.963
     1652448.983      323081.355     1652658.075      322242.268
     1652346.444        322241.4     1651731.246      323526.546
     1651189.417      323781.848     1651432.781      324964.687
     1649816.479      324393.471     1648194.332      325057.737

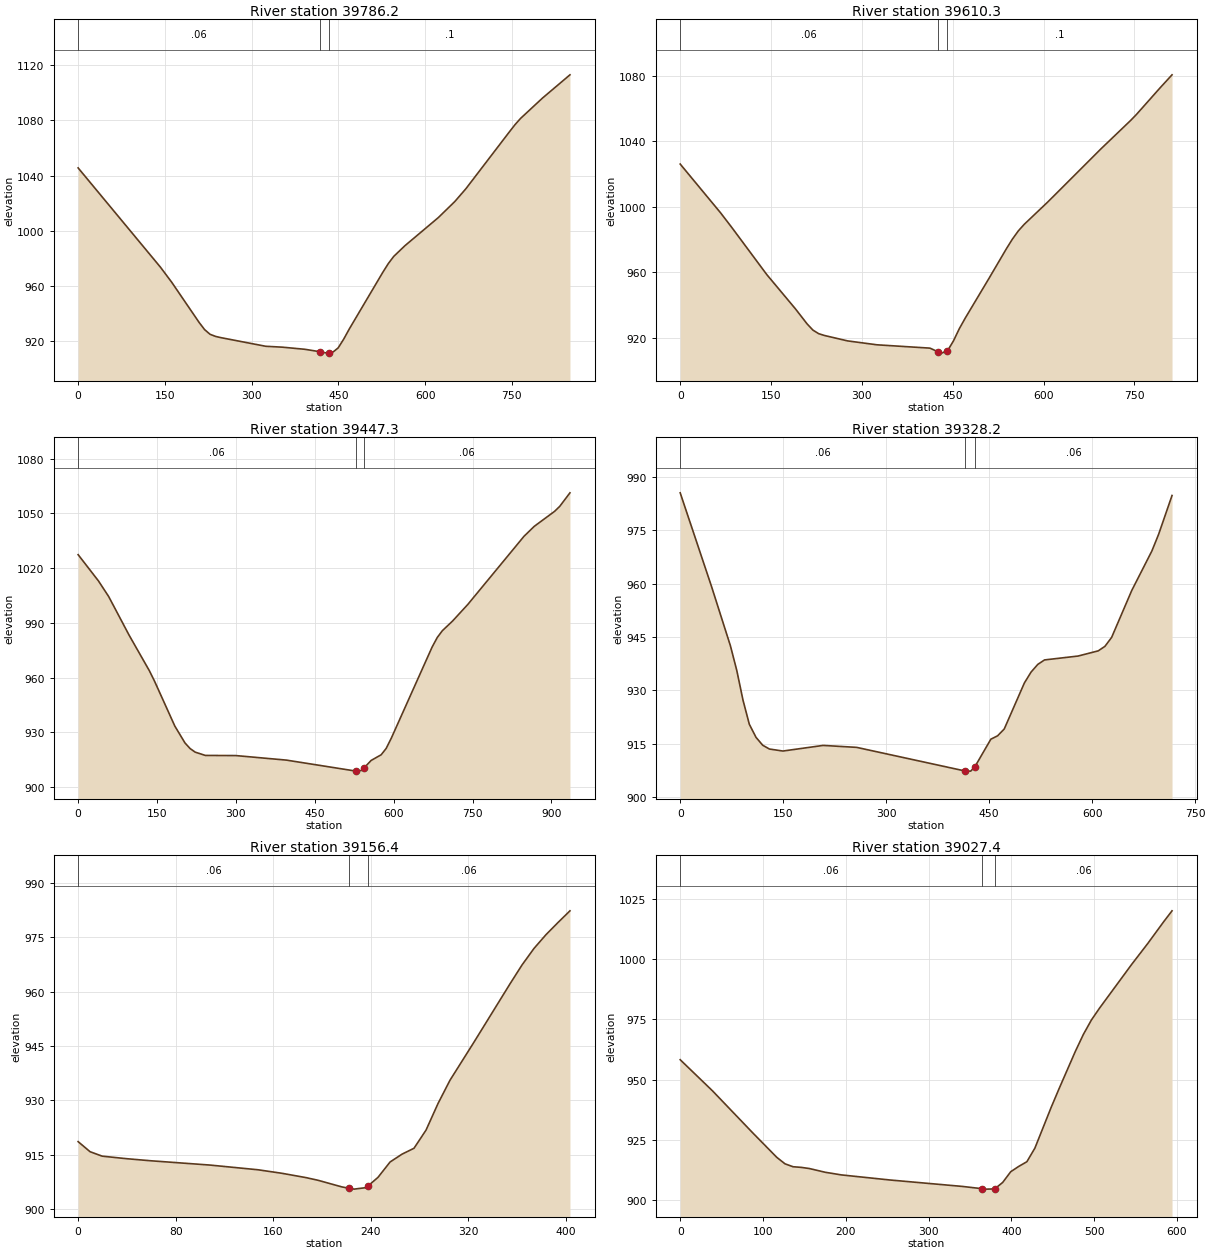
Type RM Length L Ch R = 1 ,39786.2 ,176.8,176,175.2
XS GIS Cut Line= 4
      1662872.13      303206.113     1663076.123       303308.11
     1663462.408      303427.467     1663679.422      303446.999
#Sta/Elev= 30
       0 1045.61   142.5  973.64   161.6  962.93   209.1  933.78   218.6  928.55
   228.1  925.13   237.7  923.59   247.3  922.67   324.3  916.46   353.2  915.81
   391.7  914.29   418.4   912.5   430.2   911.5   433.4  911.67   439.8     912
   449.5  915.26   459.1   921.6   468.7  928.92   526.5  969.84   536.1  976.24
   545.7  981.56     565  989.29   622.8 1009.67   651.3  1021.3   670.3 1030.49
   746.1 1071.99   755.5 1077.02     765 1081.48   802.9 1096.21   850.3 1113.01
#Mann= 3 , 0 , 0
       0     .06       0   418.4    .045       0   433.4      .1       0
Bank Sta=418.4,433.4
XS Rating Curve= 0 ,0
Exp/Cntr=0.3,0.1

Type RM Length L Ch R = 1 ,39610.3 ,165.4,163,160.6
XS GIS Cut Line= 4
     1662882.981      303297.259     1663073.953      303496.912
     1663327.859      303564.186     1663599.127      303531.634
#Sta/Elev= 30
       0 1026.06    66.7  996.34    85.7  987.18   142.9  958.76   190.5  937.74
   209.6  928.66   219.1  924.92   228.6  922.72   238.2  921.61   276.3  918.32
   324.9  915.93   412.5   913.9   425.8  911.67   431.9  910.86   440.8  912.28
   441.7  912.42   451.4  918.43   461.1  925.88   470.8  932.26   509.8  956.33
     539  974.66   548.7  980.39   558.5  985.39   568.2  989.36   607.2 1003.02
   695.1 1035.42   743.9 1052.65   753.6 1056.35   792.6 1072.55   812.2 1080.43
#Mann= 3 , 0 , 0
       0     .06       0   425.8    .045       0   440.8      .1       0
Bank Sta=425.8,440.8
XS Rating Curve= 0 ,0
Exp/Cntr=0.3,0.1

Type RM Length L Ch R = 1 ,39447.3 ,121.9,119.1,116
XS GIS Cut Line= 4
     1662852.599      303353.683     1663006.679      303666.183
     1663241.054      303703.075     1663581.766       303624.95
#Sta/Elev= 30
       0  1027.4    38.7 1012.99    58.1 1004.44    96.8  983.34   135.5  963.76
   145.2  958.12   183.9  933.43   203.2   924.2   212.9  921.14   222.6  919.16
     242  917.36     300  917.28   395.9   914.8   528.5  908.76   538.2  909.11
   543.5  910.47   557.2  914.63   576.2  917.72   585.7  921.19   595.4  926.76
   673.1  976.76   682.8  981.96   692.5  985.71   711.9     991     741 1000.13
   847.8 1037.46   867.3 1042.92   906.1 1051.17   915.8 1053.89   935.2 1061.29
#Mann= 3 , 0 , 0
       0     .06       0   528.5    .045       0   543.5     .06       0
Bank Sta=528.5,543.5
XS Rating Curve= 0 ,0
Exp/Cntr=0.3,0.1

Type RM Length L Ch R = 1 ,39328.2 ,176.1,171.8,167.5
XS GIS Cut Line= 3
     1662810.932      303873.648     1662883.849      303804.203
       1663499.3      303820.262
#Sta/Elev= 30
       0  985.58    45.8  959.14    73.2  942.53    82.4  935.64    91.5  927.26
   100.7  920.49   110.5   916.8   120.2   914.6     130  913.53   149.6  912.97
   208.2  914.55     257     914   414.4  907.38   423.2  907.32   429.4  908.61
   452.5   916.3   462.3  917.25     472  919.17   501.4  932.14   511.1  935.18
   520.9  937.34   530.7  938.59   579.5  939.68   608.9  941.14   618.6   942.4
   628.4  944.92   657.7  958.11     687  969.21   696.8  973.88   716.4  984.83
#Mann= 3 , 0 , 0
       0     .06       0   414.4    .045       0   429.4     .06       0
Bank Sta=414.4,429.4
XS Rating Curve= 0 ,0
Exp/Cntr=0.3,0.1

Type RM Length L Ch R = 1 ,39156.4 ,128.8,129,129.2
XS GIS Cut Line= 2
     1663001.522      304018.985     1663399.474      303953.509
#Sta/Elev= 29
       0  918.62     9.8  915.84    19.7  914.62    39.4  913.93      59  913.36
   108.2  912.16   147.6  910.86   167.2  909.89   186.9   908.7   196.7  907.97
   216.4  906.13   222.4  905.76   226.2  905.53   236.1  905.94   237.4  906.32
   245.9  908.78   255.8  913.01   265.6  915.17   275.4  916.79   285.3  921.81
   295.1  929.12   304.9  935.53   324.6  946.04   354.1  962.09     364  967.32
   373.8  971.87   383.6  975.65   393.5  979.02   403.3  982.24
#Mann= 3 , 0 , 0
       0     .06       0   222.4    .045       0   237.4     .06       0
Bank Sta=222.4,237.4
XS Rating Curve= 0 ,0
Exp/Cntr=0.3,0.1

Type RM Length L Ch R = 1 ,39027.4 ,100.8,100.7,100.6
XS GIS Cut Line= 2
     1662878.641      304167.051     1663465.446      304075.037
#Sta/Elev= 30
       0  958.32      39  945.42    87.6     928   116.8   917.8   126.6  915.16
   136.3  913.95   146.1  913.69   155.8  913.22   175.3  911.65   194.8  910.56
   253.2  908.46   340.8  905.79   364.8  904.84     370  904.67   379.8  904.75
   389.5  907.45   399.2  911.89     409  914.12   418.7  916.04   428.4  921.69
   447.9  938.46   457.6  946.33   477.1  961.68   486.9   968.8   496.6  974.78
   506.3  979.64   545.3  997.86   564.8 1006.56   584.2 1015.66     594 1020.05
#Mann= 3 , 0 , 0
       0     .06       0   364.8    .045       0   379.8     .06       0
Bank Sta=364.8,379.8
XS Rating Curve= 0 ,0
Exp/Cntr=0.3,0.1

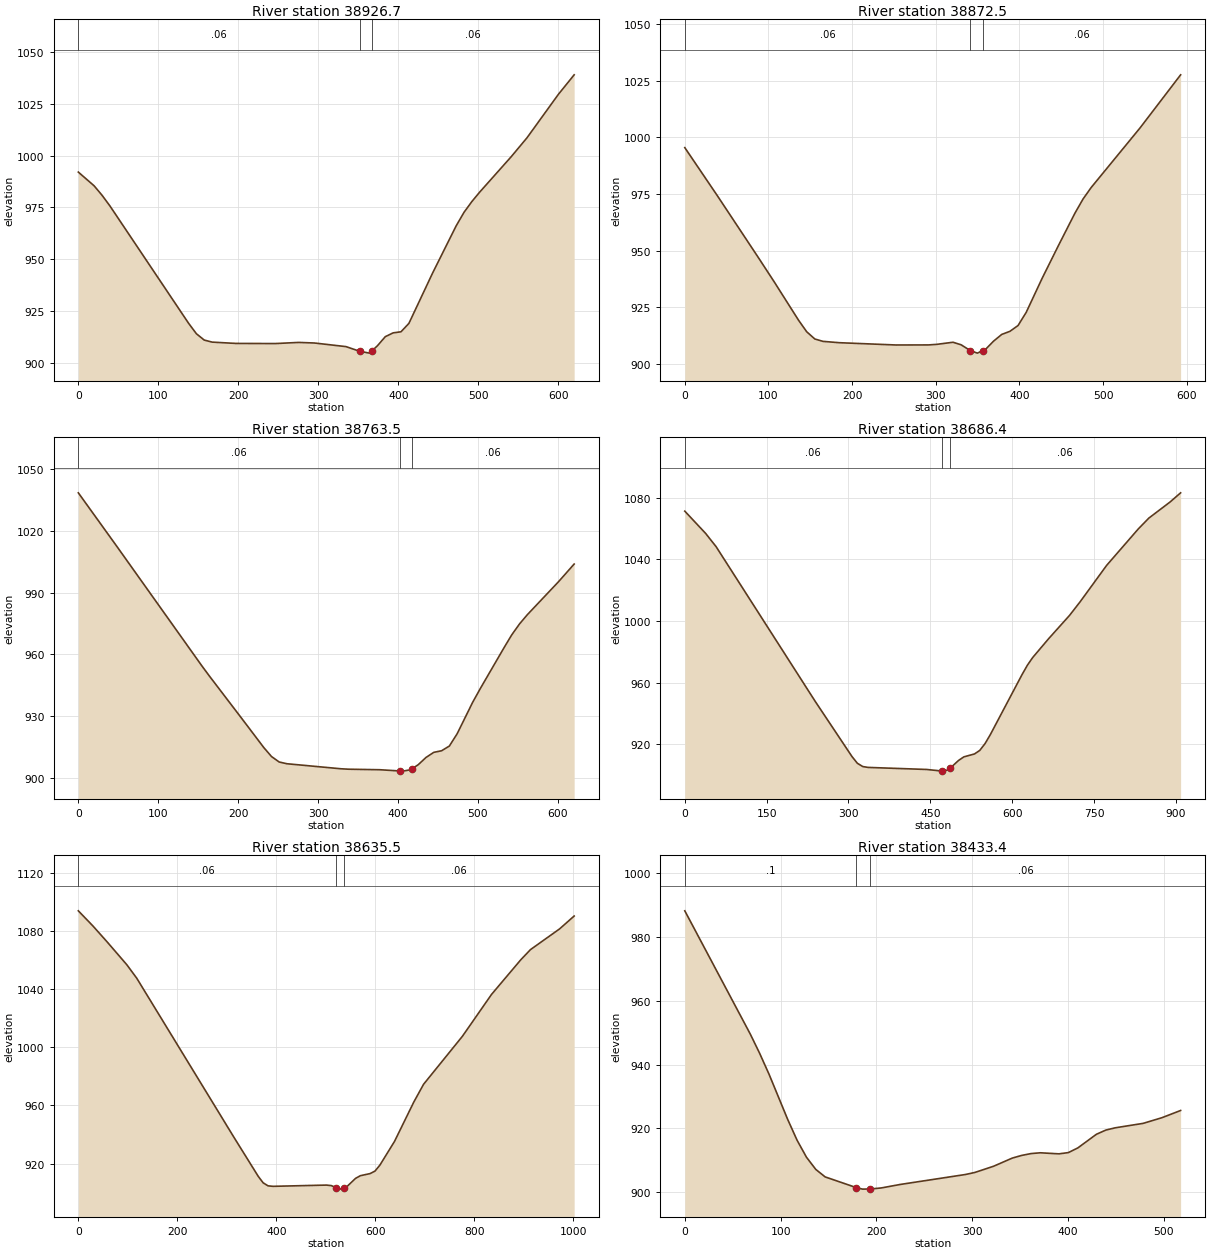
Type RM Length L Ch R = 1 ,38926.7 ,54.6,54.2,53.8
XS GIS Cut Line= 2
     1662905.279      304266.522     1663517.258      304167.563
#Sta/Elev= 30
       0  992.05    19.7  985.44    29.5  980.93    39.4  975.76   137.8  919.04
   147.6  913.96   157.4   910.9   167.3  909.91   196.8  909.28     246  909.21
   275.5  909.76   295.2  909.48   334.6  907.74   352.1  905.44   364.1  904.59
   367.1  905.67   373.9  908.13   383.8  912.54   393.6  914.38   403.4   914.9
   413.3  918.96   442.8  943.18   472.3  966.01   482.2  972.61     492  977.81
   501.8  982.38   541.2  999.48   560.9  1008.6   600.2 1029.62   619.9 1039.04
#Mann= 3 , 0 , 0
       0     .06       0   352.1    .045       0   367.1     .06       0
Bank Sta=352.1,367.1
XS Rating Curve= 0 ,0
Exp/Cntr=0.3,0.1

Type RM Length L Ch R = 1 ,38872.5 ,110.6,109,107.4
XS GIS Cut Line= 2
     1662926.112      304323.813     1663509.445      304219.647
#Sta/Elev= 30
       0  995.44    38.9  974.23    87.4  947.22   106.9   936.2     136  919.27
   145.7   914.2   155.4  911.01   165.1  909.96   184.6  909.37   252.6  908.36
   291.4  908.39   301.1  908.64   320.6  909.57   330.3  908.44   341.2  905.89
   349.7  904.77   356.2  905.88   359.4  906.42   369.1  910.08   378.8  913.02
   388.6  914.39   398.3  916.95     408  922.73   427.4  938.02   446.8   952.4
   466.3  966.53     476  972.78   485.7  977.84     544 1004.09   592.6 1027.56
#Mann= 3 , 0 , 0
       0     .06       0   341.2    .045       0   356.2     .06       0
Bank Sta=341.2,356.2
XS Rating Curve= 0 ,0
Exp/Cntr=0.3,0.1

Type RM Length L Ch R = 1 ,38763.5 ,78.2,77.1,76
XS GIS Cut Line= 3
     1662894.862      304469.647     1663316.737      304362.876
     1663478.195       304271.73
#Sta/Elev= 30
       0  1038.6    48.4 1012.45   154.7  954.41   164.4  949.32   203.1  929.62
   232.1  914.74   241.8  910.35   251.4   907.7   261.1  906.85   328.8   904.4
   338.5  904.19   377.2  903.94   402.7  903.33   406.2  903.26   415.8  903.93
   417.7  904.41   425.5   906.4   435.2  909.92   444.9  912.39   454.7  913.17
   464.4  915.46   474.2  921.47   493.7  936.83   503.5  943.67   532.8  963.26
   542.5  969.54   552.3  974.88     562  979.33   601.1   995.4   620.6 1003.96
#Mann= 3 , 0 , 0
       0     .06       0   402.7    .045       0   417.7     .06       0
Bank Sta=402.7,417.7
XS Rating Curve= 0 ,0
Exp/Cntr=0.3,0.1

Type RM Length L Ch R = 1 ,38686.4 ,50.8,50.9,51
XS GIS Cut Line= 4
     1662852.599      304584.151     1663117.356      304501.686
     1663350.883      304431.199     1663651.478      304186.758
#Sta/Elev= 30
       0 1071.33    38.2 1056.88    57.4 1048.28     239  947.92   306.6  912.02
   316.3  907.74   326.1  905.63   335.8  905.06   443.2  903.73     471  902.71
   472.4  902.65   482.2  903.39     486  904.46   501.7  909.57   511.5  911.91
   530.9  913.79   540.6  916.09   550.3  920.52     560  926.37   618.1   965.3
   627.8  971.33   637.5  976.32   666.5  988.45   705.3 1003.76   724.6 1012.56
   773.1 1036.14   831.2 1059.82   850.6 1066.86   889.3 1077.25   908.7 1083.22
#Mann= 3 , 0 , 0
       0     .06       0     471    .045       0     486     .06       0
Bank Sta=471,486
XS Rating Curve= 0 ,0
Exp/Cntr=0.3,0.1

Type RM Length L Ch R = 1 ,38635.5 ,199.5,202.1,203.5
XS GIS Cut Line= 3
     1662807.026      304644.915     1663390.793      304471.304
     1663705.464      304236.929
#Sta/Elev= 30
       0 1093.88    29.5 1083.46    58.9 1072.22    98.2 1056.68   117.9 1047.56
   314.3  938.05   363.5  911.13   373.3  906.74   383.1  904.67   392.9  904.32
     501  905.18   510.8  904.83   520.8  903.42   530.4   902.4   535.8  902.97
   540.3  903.44   559.9   909.8   569.7  911.64   589.4   913.1   599.2  914.84
     609  918.89   638.5  935.18   677.7  962.42   697.3  974.55   775.8  1007.6
   834.6  1036.4   893.5 1060.15   913.1 1067.17     972 1081.45  1001.4 1090.31
#Mann= 3 , 0 , 0
       0     .06       0   520.8    .045       0   535.8     .06       0
Bank Sta=520.8,535.8
XS Rating Curve= 0 ,0
Exp/Cntr=0.3,0.1

Type RM Length L Ch R = 1 ,38433.4 ,317.6,317.2,316.9
XS GIS Cut Line= 2
      1663043.58      304699.106     1663553.041      304607.633
#Sta/Elev= 30
       0  988.22    68.4  949.53    78.1  943.54    87.9  936.99   107.4  922.79
   117.2  916.26     127  910.93   136.7  907.11   146.5  904.75   178.8  901.41
   185.6  900.91   193.8  900.95   205.1  901.28   224.6  902.36     293   905.5
   302.8  906.14   322.3  908.08   341.8  910.64   351.6  911.48   361.4  912.06
   371.1  912.31   390.6  911.98   400.4  912.37   410.2  913.82   429.7  918.12
   439.5  919.43   449.2  920.14   478.5  921.54   498.1  923.32   517.6  925.58
#Mann= 3 , 0 , 0
       0      .1       0   178.8    .045       0   193.8     .06       0
Bank Sta=178.8,193.8
XS Rating Curve= 0 ,0
Exp/Cntr=0.3,0.1

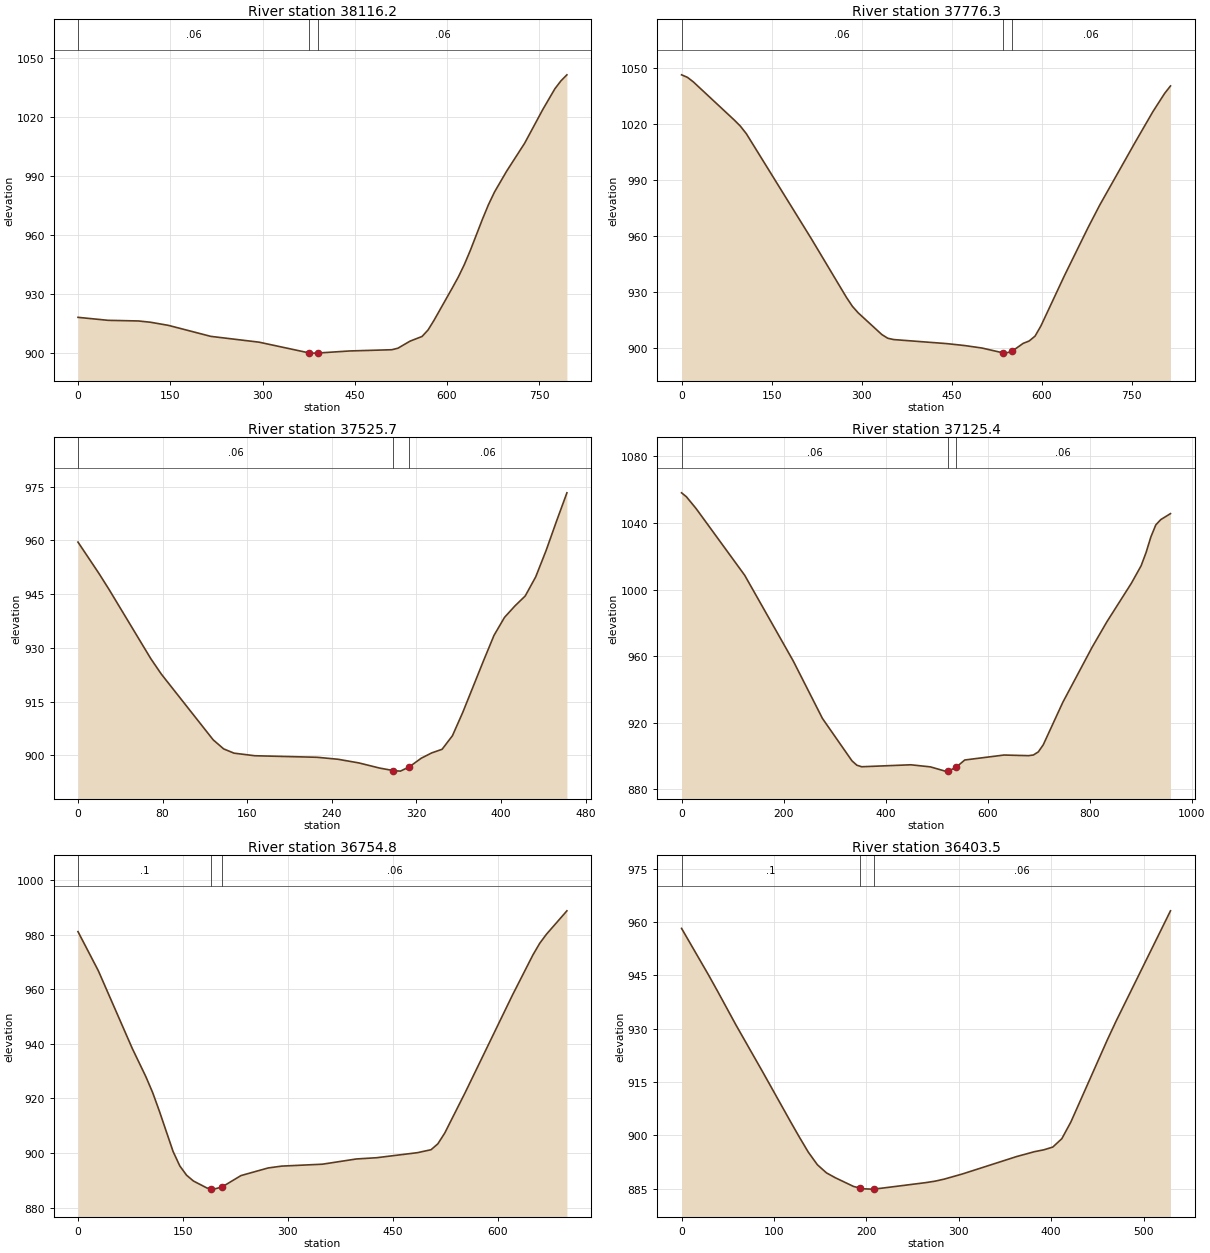
Type RM Length L Ch R = 1 ,38116.2 ,352.7,339.9,326.1
XS GIS Cut Line= 2
     1662930.724      305050.731     1663705.464       304872.78
#Sta/Elev= 30
       0  918.09    49.1  916.57    98.1  916.25   117.8   915.6   147.2     914
   215.9  908.42   294.4  905.47   375.9     900   382.7   899.9   390.9  899.97
   441.6     901   510.3  901.63   520.1  902.39   539.8  905.98   559.4  908.37
   569.2  911.69     579  916.67   608.4  932.94   618.3  938.56   628.1  944.89
   637.9  952.14   657.5  967.91   667.3  975.32   677.2   981.8   696.8  992.33
   726.2  1006.6   755.7 1023.74   775.3 1034.24   785.1 1038.26   794.9 1041.36
#Mann= 3 , 0 , 0
       0     .06       0   375.9    .045       0   390.9     .06       0
Bank Sta=375.9,390.9
XS Rating Curve= 0 ,0
Exp/Cntr=0.3,0.1

Type RM Length L Ch R = 1 ,37776.3 ,250.5,250.6,250.7
XS GIS Cut Line= 2
     1663112.633      305555.877     1663720.272      305013.343
#Sta/Elev= 30
       0 1046.34     9.8 1044.99    19.6 1042.55    88.3 1021.94    98.1 1018.77
     108 1014.71   215.9  958.56   274.8  926.88   284.6  922.14   294.4  918.59
   333.7  906.97   343.5  905.01   353.3  904.29   441.6  902.12   471.1   901.1
   500.5  899.75   535.1  897.19   539.8  897.01   550.1  897.91   569.2  902.26
     579   903.5   588.9  906.12   598.7   911.6   637.9  938.58   677.2  964.33
   696.8  976.51   755.7 1010.12   785.2 1026.54   804.8 1036.36   814.6 1040.37
#Mann= 3 , 0 , 0
       0     .06       0   535.1    .045       0   550.1     .06       0
Bank Sta=535.1,550.1
XS Rating Curve= 0 ,0
Exp/Cntr=0.3,0.1

Type RM Length L Ch R = 1 ,37525.7 ,398.1,400.3,401.8
XS GIS Cut Line= 2
      1663450.61      305587.234     1663796.964      305281.244
#Sta/Elev= 30
       0  959.51    19.7  950.82    29.5  946.24    68.8  927.02    78.7  922.73
   127.8  904.37   137.7  901.84   147.5  900.65   167.2  899.93   226.2   899.5
   245.8  898.95   265.5  897.93   285.2  896.49   298.1  895.79   304.8  895.64
   313.1  896.81   324.5  899.24   334.3  900.71   344.2  901.73     354  905.52
   363.8  912.06   383.5  926.52   393.3  933.51   403.2  938.51     413  941.69
   422.8  944.49   432.7  949.81   442.5  957.14   452.3  965.28   462.2  973.25
#Mann= 3 , 0 , 0
       0     .06       0   298.1    .045       0   313.1     .06       0
Bank Sta=298.1,313.1
XS Rating Curve= 0 ,0
Exp/Cntr=0.3,0.1

Type RM Length L Ch R = 1 ,37125.4 ,358.2,370.5,383.3
XS GIS Cut Line= 4
     1663533.206      305952.145       1663749.3      305795.957
     1664046.609      305583.283     1664147.355      305272.891
#Sta/Elev= 30
       0 1058.11     9.5 1055.74    28.6 1048.62   123.8 1008.57     219  957.07
   276.2  922.57     334  897.14   343.6  894.49   353.2  893.56   449.4  894.74
   487.9  893.48   516.7  890.93     523  890.96     538  893.21   555.2  897.62
   632.2   900.6   680.2  900.22   689.8  900.63   699.4   902.5     709  906.71
   747.4  932.26   804.9  965.38   833.7  980.59   881.7 1003.74   900.9 1014.28
   910.5 1022.13   920.1 1031.67   929.7 1038.83   939.3    1042   958.5 1045.62
#Mann= 3 , 0 , 0
       0     .06       0     523    .045       0     538     .06       0
Bank Sta=523,538
XS Rating Curve= 0 ,0
Exp/Cntr=0.3,0.1

Type RM Length L Ch R = 1 ,36754.8 ,352.6,351.4,348.9
XS GIS Cut Line= 2
     1663721.444      305979.161      1664419.36      305942.702
#Sta/Elev= 30
       0  981.16    29.1  966.81    77.6  938.33    97.1  927.94   106.8  922.11
   116.5  915.23   135.9  900.57   145.6  895.22   155.3  891.83     165  889.72
   184.4  887.15   190.7  886.88   194.1  886.74   205.7   887.5     233  891.71
   271.8   894.5   291.2  895.18   349.4  895.88     398   897.8   427.1  898.26
   485.3  900.11   504.7  901.19   514.4  903.34   524.2  907.27   553.3  922.06
   621.2  957.96   650.3  972.61     660  976.87   669.8  980.25   698.9  988.79
#Mann= 3 , 0 , 0
       0      .1       0   190.7    .045       0   205.7     .06       0
Bank Sta=190.7,205.7
XS Rating Curve= 0 ,0
Exp/Cntr=0.3,0.1

Type RM Length L Ch R = 1 ,36403.5 ,227.7,226.2,224.4
XS GIS Cut Line= 2
     1663792.703       306318.96     1664318.311      306257.762
#Sta/Elev= 30
       0  958.22    29.4  945.02    39.2  940.44    58.8  931.08    88.2  917.66
   117.6     904   127.4  899.54   137.2  895.26     147  891.72   156.8  889.44
   166.6  888.04   186.2  885.61   192.9  885.17     196  884.96   205.8  884.86
   207.9  884.91   215.6  885.09   264.6   886.7   274.4   887.1   284.2  887.67
   303.8  889.11   362.6  894.02   382.2  895.41     392  895.91   401.8  896.69
   411.6  899.06   421.4  903.76   460.6  926.72   470.4  932.17   529.2  963.16
#Mann= 3 , 0 , 0
       0      .1       0   192.9    .045       0   207.9     .06       0
Bank Sta=192.9,207.9
XS Rating Curve= 0 ,0
Exp/Cntr=0.3,0.1

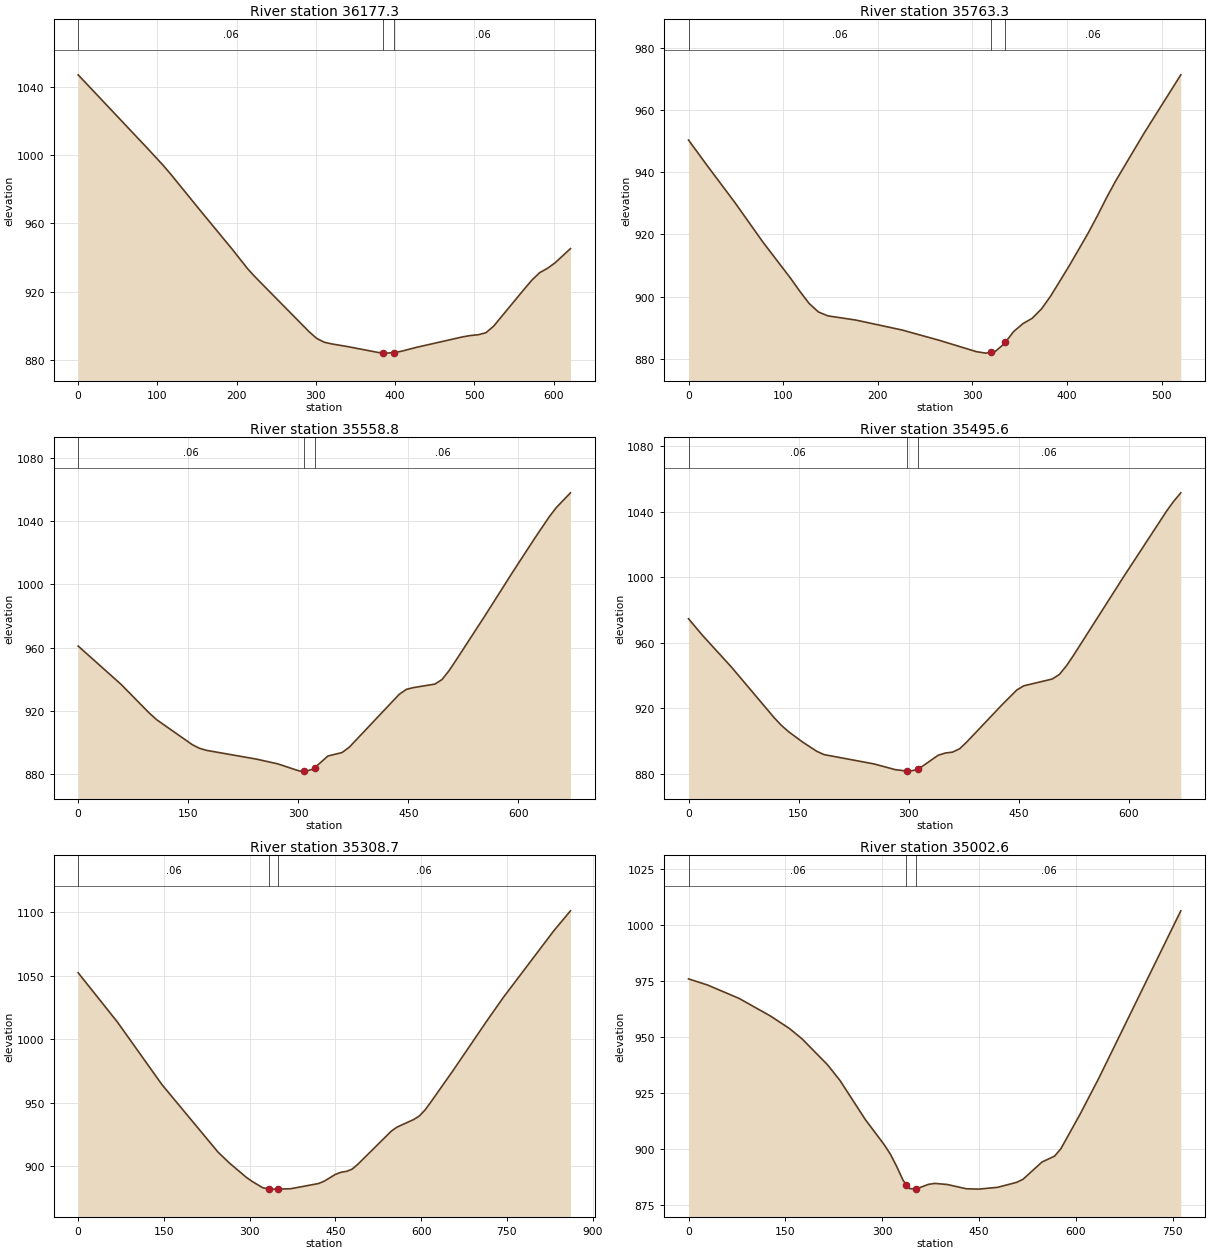
Type RM Length L Ch R = 1 ,36177.3 ,405.6,413.9,421
XS GIS Cut Line= 2
     1663691.626      306543.725     1664307.381      306460.931
#Sta/Elev= 30
       0 1047.17    87.4  1004.1   106.8  994.34   116.5  989.11   155.3  966.93
   194.2  945.03   213.6  933.61   223.3  928.67   291.2  896.64   300.9  892.63
   310.6  890.34   320.4  889.33   339.8  887.82   378.6  884.35   384.1  884.13
   388.3  883.96   399.1  884.26   407.7  885.04   427.1  887.36   485.4  893.51
   495.1  894.29   504.8  894.73   514.5   895.9   524.2  899.69     563  921.51
   572.8  926.86   582.5  931.16   592.2  933.67   601.9  936.91   621.3  945.26
#Mann= 3 , 0 , 0
       0     .06       0   384.1    .045       0   399.1     .06       0
Bank Sta=384.1,399.1
XS Rating Curve= 0 ,0
Exp/Cntr=0.3,0.1

Type RM Length L Ch R = 1 ,35763.3 ,204.6,204.5,204.4
XS GIS Cut Line= 2
     1663816.141      306809.412     1664330.029      306891.009
#Sta/Elev= 30
       0  950.33    19.6  942.17    49.1  930.22    78.5   917.6     108  905.87
   117.8  901.68   127.6  897.79   137.4  895.07   147.3  893.84   176.7   892.5
   225.8  889.29   265.1  885.98   304.3  882.34   314.2  881.87   319.8  882.15
     324  882.36   333.8  884.91   334.8  885.31   343.6  888.79   353.4  891.33
   363.2  893.05   373.1  896.07   382.9  900.26   402.5  909.98   422.2  920.32
     432   925.9   441.8  931.77   451.6  937.25   481.1  952.32   520.3  971.26
#Mann= 3 , 0 , 0
       0     .06       0   319.8    .045       0   334.8     .06       0
Bank Sta=319.8,334.8
XS Rating Curve= 0 ,0
Exp/Cntr=0.3,0.1

Type RM Length L Ch R = 1 ,35558.8 ,63.7,63.3,63.1
XS GIS Cut Line= 2
     1663777.248      307010.207     1664440.442      307112.637
#Sta/Elev= 30
       0     961    58.4  936.82    97.2  918.49     107  914.41   155.6   898.6
   165.3  896.32   175.1     895   243.1  889.46   272.3  886.44   301.5  881.95
   307.8   881.9   311.2  881.87   320.9  883.28   322.8  884.13   340.4  891.42
   359.8  893.63   369.6     897   437.6  930.43   447.4  933.59   457.1  934.71
   486.3  936.92     496   939.8   505.7  945.49   515.4   952.2   554.4  980.06
   593.2  1008.4   622.4 1029.17   641.9 1042.57   651.6 1048.49   671.1 1057.93
#Mann= 3 , 0 , 0
       0     .06       0   307.8    .045       0   322.8     .06       0
Bank Sta=307.8,322.8
XS Rating Curve= 0 ,0
Exp/Cntr=0.3,0.1

Type RM Length L Ch R = 1 ,35495.6 ,189.5,186.9,183.8
XS GIS Cut Line= 2
     1663766.831       307070.97     1664430.026      307173.401
#Sta/Elev= 30
       0  974.68    19.4   964.4    58.4   945.3   116.7  914.41   126.4  909.78
   136.2  905.92   155.6   899.5   175.1  893.82   184.8  891.87   252.9  886.19
     282  882.69   297.6  881.84   301.5   881.8   312.6  882.82   340.4  891.48
   350.1  892.84   359.8  893.37   369.6  895.42   379.3  899.54   427.9  922.46
   447.4   931.2   457.1   933.8     496  937.96   505.7  940.78   515.4  946.11
   525.2   952.6   593.2  1000.3   651.6 1040.21   661.3 1046.22   671.1 1051.43
#Mann= 3 , 0 , 0
       0     .06       0   297.6    .045       0   312.6     .06       0
Bank Sta=297.6,312.6
XS Rating Curve= 0 ,0
Exp/Cntr=0.3,0.1

Type RM Length L Ch R = 1 ,35308.7 ,306.8,306.1,304.5
XS GIS Cut Line= 2
     1663661.244       307286.78     1664522.466      307297.772
#Sta/Elev= 30
       0  1052.2    68.5 1013.51   146.8  964.01   244.7  910.96   264.3   902.5
   293.6  891.32   303.4  888.14     323  882.87   334.6  881.84   342.6   881.8
   349.6   881.8   371.9  882.11   420.9  886.25   430.6  888.07   450.2  893.44
     460  895.11   469.8  895.81   479.6  897.62   489.4   901.4   548.1  927.57
   557.9  930.64   587.2  936.65     597  939.44   606.8  944.08   616.6  950.07
   655.8  975.12   714.5 1013.94   743.8 1032.73   831.9 1085.11   861.3 1100.98
#Mann= 3 , 0 , 0
       0     .06       0   334.6    .045       0   349.6     .06       0
Bank Sta=334.6,349.6
XS Rating Curve= 0 ,0
Exp/Cntr=0.3,0.1

Type RM Length L Ch R = 1 ,35002.6 ,440.2,444.1,444.8
XS GIS Cut Line= 2
     1663591.009        307592.7     1664352.727      307562.318
#Sta/Elev= 30
       0  975.79    29.3  973.07    78.2  967.09     127   959.2   156.4  953.62
   175.9     949     215  937.54   234.6  930.44   273.6  913.09     303   901.8
   312.8  897.47   322.5  891.99   332.3  885.88   337.5  883.93   342.1   882.2
   352.5  882.03   371.4  884.06   381.2   884.5   400.7  884.02     430  882.12
   449.6  881.95   478.9  882.77   508.2  884.98     518  886.35   547.3  894.03
   566.9  896.69   576.6  899.98     606   915.2   635.3  931.43   762.3 1006.16
#Mann= 3 , 0 , 0
       0     .06       0   337.5    .045       0   352.5     .06       0
Bank Sta=337.5,352.5
XS Rating Curve= 0 ,0
Exp/Cntr=0.3,0.1

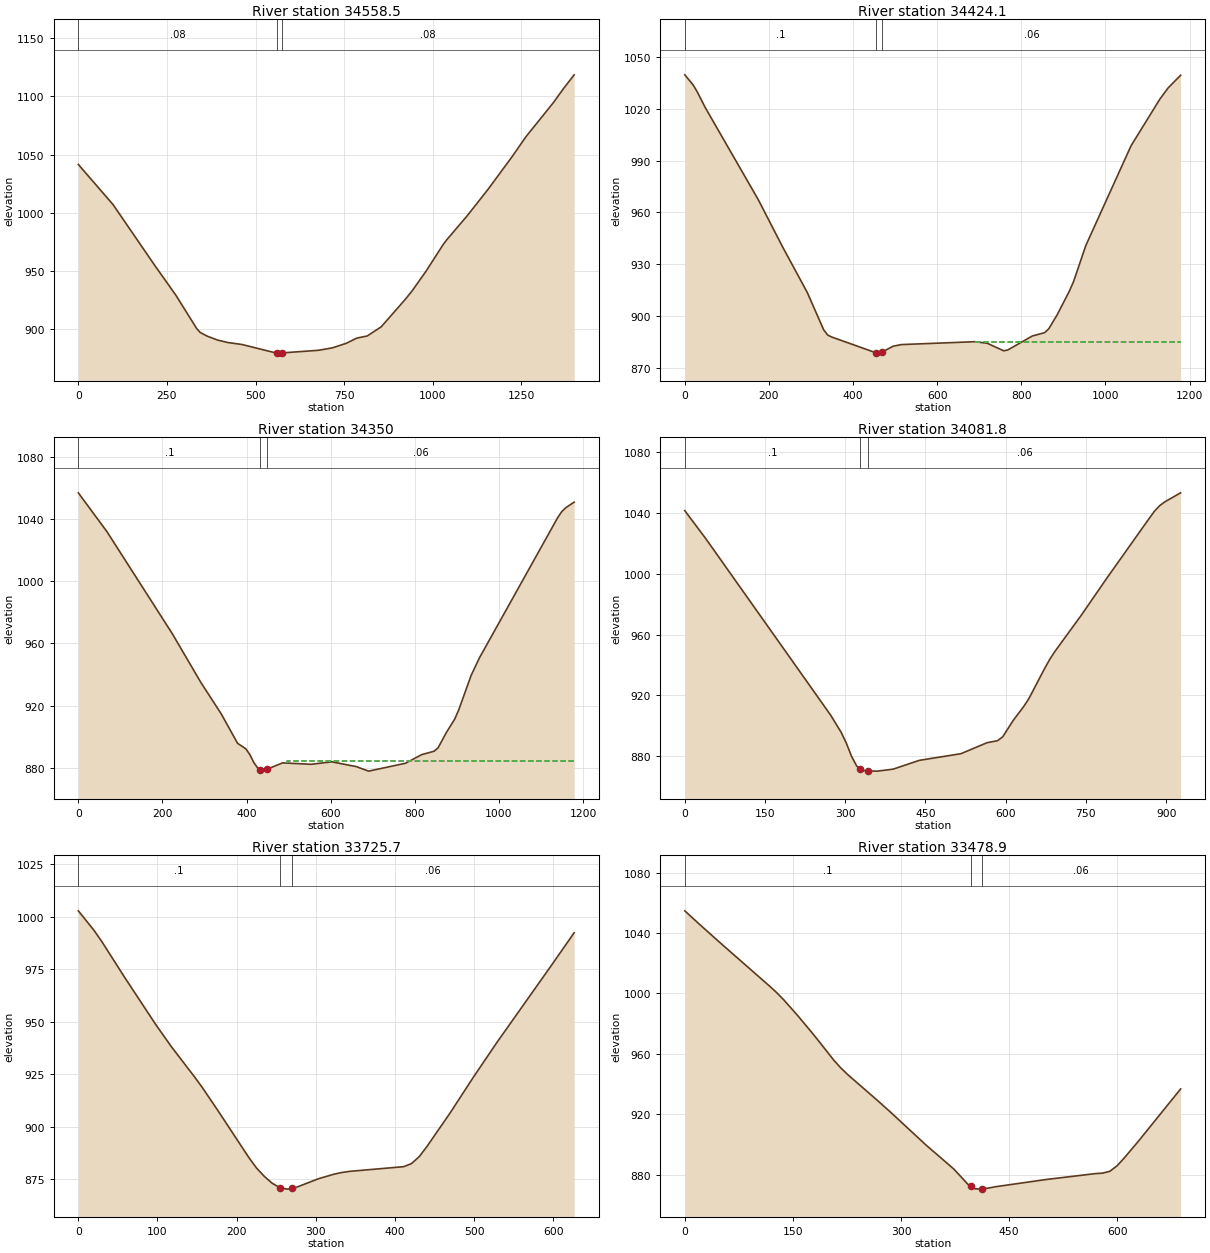
Type RM Length L Ch R = 1 ,34558.5 ,123.4,134.4,146.1
XS GIS Cut Line= 4
     1663635.202      308312.822     1663846.444      307981.765
     1664307.381      307955.723     1664607.424       307501.19
#Sta/Elev= 30
       0 1041.53    98.2 1006.92     216  954.56   274.9  929.24   333.8   900.5
   343.6  897.13   363.3  893.95   392.7  890.53   422.2  888.39   461.5  886.74
   559.6   879.3   574.6  879.49   677.6  881.74   716.9  883.84   756.2  887.76
   785.6  892.21   815.1  894.04   854.4  901.87   922.5  925.52   941.9  932.88
   980.8  949.61  1029.4  972.62  1039.2  976.62  1097.5   997.5  1155.9 1020.07
    1224 1048.23  1262.9 1065.34  1340.7 1094.78  1369.8 1107.09    1399 1118.57
#Mann= 3 , 0 , 0
       0     .08       0   559.6    .045       0   574.6     .08       0
Bank Sta=559.6,574.6
XS Rating Curve= 0 ,0
Exp/Cntr=0.3,0.1

Type RM Length L Ch R = 1 ,34424.1 ,72.9,74.1,76.6
XS GIS Cut Line= 4
     1663680.026      308341.804     1663933.498      308060.554
     1664353.637      308286.248     1664674.817      308322.707
#Sta/Elev= 30
       0 1039.61    19.4  1033.9    29.1    1030    48.5 1020.71   174.8  967.29
     233  939.76   291.2  913.61   330.1  892.03   339.8  888.96   349.5   887.8
   453.9  878.74   456.5  878.49   468.9  879.08   495.4   882.5   514.9  883.44
   690.1  885.11   719.3  884.18   758.2  879.83   767.9  880.32   826.3  888.41
   855.5  890.35   865.3  892.56   884.9  900.49   914.3  914.38   924.1   919.8
   953.5  940.84  1061.2  998.66  1129.8 1025.68  1149.4 1032.12  1178.8 1039.37
#Mann= 3 , 0 , 0
       0      .1       0   453.9    .045       0   468.9     .06       0
#XS Ineff= 2 , 0
                          689.22           885.2
Permanent Ineff=
       F       F
Bank Sta=453.9,468.9
XS Rating Curve= 0 ,0
Exp/Cntr=0.3,0.1

Type RM Length L Ch R = 1 ,34350   ,282.8,268.1,251.1
XS GIS Cut Line= 4
     1663685.234      308423.401     1663938.706      308142.151
     1664358.845      308367.845     1664680.026      308404.304
#Sta/Elev= 30
       0 1056.95      68 1031.98   223.3  966.34   291.2  934.97   339.8  914.67
   378.6  895.74   398.1  892.24   407.8   888.5   417.6  883.22   427.3  879.54
   432.4  878.88   447.4  878.94   485.7  883.17   553.8  882.24   602.5  883.85
   660.9  880.75   690.1  877.85   777.7  882.92   816.6   888.5   845.8  890.65
   855.5  892.92   875.1  902.77   894.7  911.25   904.5  917.33   933.9  939.49
   953.5  950.68  1139.6 1040.96  1149.4 1044.89  1159.2 1047.44  1178.8 1050.95
#Mann= 3 , 0 , 0
       0      .1       0   432.4    .045       0   447.4     .06       0
#XS Ineff= 2 , 0
                           496.9          884.09
Permanent Ineff=
       F       F
Bank Sta=432.4,447.4
XS Rating Curve= 0 ,0
Exp/Cntr=0.3,0.1

Type RM Length L Ch R = 1 ,34081.8 ,352,356.2,360.3
XS GIS Cut Line= 4
     1663782.772      308512.475     1664078.293      308413.578
     1664349.127      308378.856      1664689.89      308412.648
#Sta/Elev= 30
       0 1041.46      39  1023.2   272.7  907.03   292.2  895.83   301.9  888.74
   311.6  880.09   321.4  873.58   327.8  871.77   331.1  870.84   342.8  870.27
   360.4   870.2   389.6   871.5   438.4  877.28   516.4  881.67   565.2   888.9
   584.7  890.19   594.5  892.78     614  903.52   633.6  912.64   643.4  917.89
   672.7  937.62   682.5  943.76   692.3  949.03   741.2  972.64   790.1  997.58
   868.4  1036.4   878.2 1041.12     888  1044.8   897.8 1047.32   927.1  1053.2
#Mann= 3 , 0 , 0
       0      .1       0   327.8    .045       0   342.8     .06       0
Bank Sta=327.8,342.8
XS Rating Curve= 0 ,0
Exp/Cntr=0.3,0.1

Type RM Length L Ch R = 1 ,33725.7 ,243.3,246.7,250
XS GIS Cut Line= 2
     1663942.571      308729.853     1664567.571      308771.086
#Sta/Elev= 30
       0 1002.83    19.6  993.64    29.4  988.36    58.7  971.05    97.9  948.65
   117.4  938.23   146.8  923.79   156.6  918.73   176.2  907.83   215.3  885.45
   225.1   880.4   234.9  876.44   244.7   873.2   254.6  870.98   264.2  870.34
   269.6   870.7     274  870.99   303.4  875.29     323  877.46   332.8  878.25
   342.5  878.79     411  881.03   420.8  882.48   430.6  885.77   440.4  890.62
   469.8  906.67   499.1  923.63   528.5  940.01     597   976.5   626.4   992.4
#Mann= 3 , 0 , 0
       0      .1       0   254.6    .045       0   269.6     .06       0
Bank Sta=254.6,269.6
XS Rating Curve= 0 ,0
Exp/Cntr=0.3,0.1

Type RM Length L Ch R = 1 ,33478.9 ,270.6,270.2,269.1
XS GIS Cut Line= 2
      1663752.39      308898.759     1664424.569      309044.265
#Sta/Elev= 30
       0 1054.71    19.6 1046.13    49.1 1033.54   117.9 1004.76   127.7 1000.46
   137.6  995.62   157.2  985.05   176.8  973.82   186.7  967.97   206.3  956.08
   216.2   950.8     226  946.31   265.3     930   284.9  921.66     334  899.93
   373.4  883.69     393  873.54   396.7  872.46   402.8  870.69   411.7   870.5
   412.6  870.48   432.3  872.16   501.1  876.84   569.8  880.77   579.7  881.07
   589.5  882.27   599.3  885.77   609.2  890.88   628.8  901.95   687.8   936.8
#Mann= 3 , 0 , 0
       0      .1       0   396.7    .045       0   411.7     .06       0
Bank Sta=396.7,411.7
XS Rating Curve= 0 ,0
Exp/Cntr=0.3,0.1

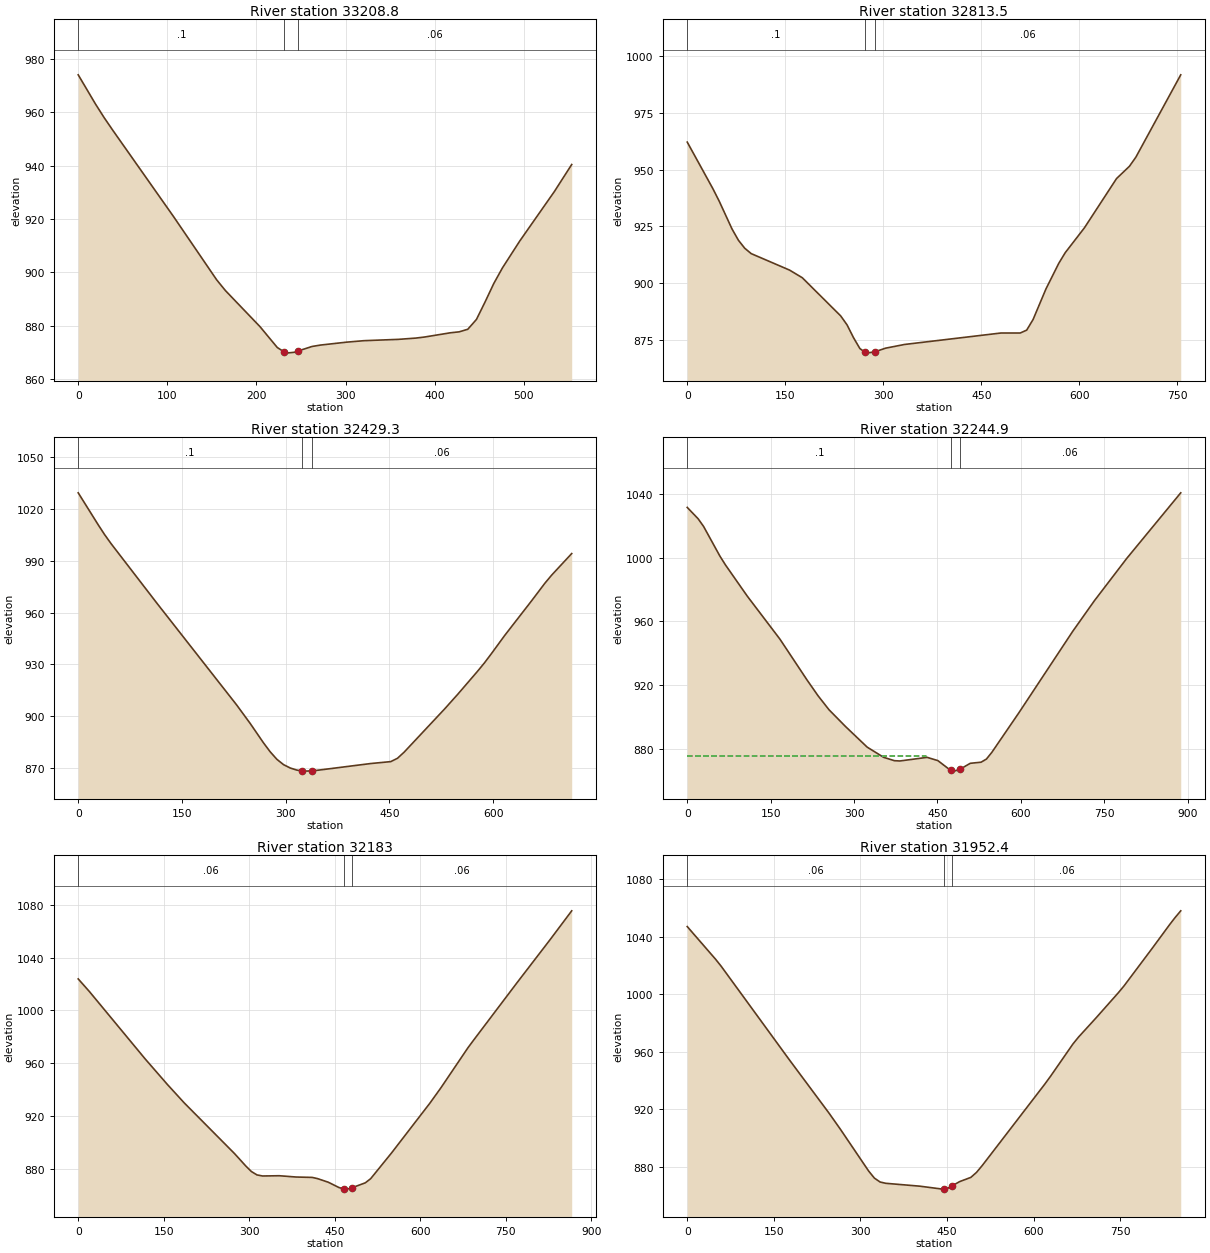
Type RM Length L Ch R = 1 ,33208.8 ,397.4,395.2,392.2
XS GIS Cut Line= 2
     1663829.724      309196.433     1664374.429      309296.259
#Sta/Elev= 30
       0  974.11    19.4  963.14    29.2  957.99    38.9  953.25   106.9  920.93
   155.4  897.14   165.2  893.11     204  879.57   223.4  871.74   231.3  870.04
   233.2  869.63   242.9  869.96   246.3  870.38   262.3  872.12     272  872.66
   301.2  873.75   320.6   874.3   359.5   874.8   378.9  875.28   388.6  875.67
   417.8  877.27   427.5  877.62   437.2  878.59   446.9  882.28   456.6  888.85
   466.3  895.73     476  901.59   495.5  911.72   534.4  930.32   553.8  940.44
#Mann= 3 , 0 , 0
       0      .1       0   231.3    .045       0   246.3     .06       0
Bank Sta=231.3,246.3
XS Rating Curve= 0 ,0
Exp/Cntr=0.3,0.1

Type RM Length L Ch R = 1 ,32813.5 ,392.9,384.2,373.3
XS GIS Cut Line= 3
     1663710.238      309604.551     1664022.524      309626.745
     1664463.876      309602.225
#Sta/Elev= 30
       0  962.06    39.1  941.65    48.9  936.08    68.5  923.86    78.3  918.89
      88  915.37    97.8  913.02   156.5  905.77   176.1  902.39   234.8  885.61
   244.6  881.64   254.4  876.04   264.2  871.24     272  869.63   273.9  869.24
     287   869.8   303.3  871.41   332.7  873.06   480.1  878.09   509.5  878.09
   519.4  879.36   529.2  884.05   548.8  897.43   568.5  908.75   578.3   913.4
   607.8  924.39   656.9  946.04   676.5   951.4   686.4  955.42   755.1  991.66
#Mann= 3 , 0 , 0
       0      .1       0     272    .045       0     287     .06       0
Bank Sta=272,287
XS Rating Curve= 0 ,0
Exp/Cntr=0.3,0.1

Type RM Length L Ch R = 1 ,32429.3 ,186.4,184.4,182.9
XS GIS Cut Line= 4
     1663859.977      310023.387      1664055.29      309979.985
     1664306.426      309877.408     1664545.307       309837.19
#Sta/Elev= 30
       0 1029.35    28.6 1011.04    38.1  1005.2    47.6  999.89   114.3   965.2
   229.1  906.56   248.5  895.95   267.9  884.63   277.6  879.44   287.3  875.08
     297  871.98   306.6  870.06   316.3  868.82   323.4   868.4     326  868.25
   338.4  868.36   422.9  872.64     452  873.76   461.7  875.69   471.4  879.28
   529.5   904.1   548.9  912.77   577.9  926.27   587.6  931.01   597.3  936.15
   616.7  946.78   655.5   966.8   674.8  977.01   684.5  981.66   713.6   994.2
#Mann= 3 , 0 , 0
       0      .1       0   323.4    .045       0   338.4     .06       0
Bank Sta=323.4,338.4
XS Rating Curve= 0 ,0
Exp/Cntr=0.3,0.1

Type RM Length L Ch R = 1 ,32244.9 ,58.3,61.9,64.7
XS GIS Cut Line= 4
     1663855.373      310295.363     1664231.071      310103.683
     1664389.491      310029.898      1664678.12      309990.835
#Sta/Elev= 30
       0 1031.46    19.6 1024.32    29.4 1019.51    58.8 1000.86    68.7  995.37
   107.9  975.79   166.8  948.71   215.8  922.94   235.4  913.14     255  904.41
   284.4  893.98   323.7  880.92   353.1  874.55   372.7   872.4   382.5  872.22
   431.5   874.5   450.9  872.45   470.3  867.27   475.2  866.55     480  865.85
   490.2  866.94   509.2  870.77   528.6  871.45   538.3  873.45     548  877.66
   596.5  902.43   693.6   953.7   732.4  972.83   790.7  999.45   887.8 1040.62
#Mann= 3 , 0 , 0
       0      .1       0   475.2    .045       0   490.2     .06       0
#XS Ineff= 2 , 0
          429.58  875.43
Permanent Ineff=
       F       F
Bank Sta=475.2,490.2
XS Rating Curve= 0 ,0
Exp/Cntr=0.3,0.1

Type RM Length L Ch R = 1 ,32183   ,224.6,230.6,237.2
XS GIS Cut Line= 4
     1663887.925      310345.276     1664231.071      310155.766
     1664391.661      310108.023     1664697.651      310097.172
#Sta/Elev= 30
       0 1023.86    19.6 1014.33   117.6  963.31   156.8   943.9   186.2  930.06
   274.4  891.75     294  882.44   303.8  878.27   313.6  875.71   323.4   874.9
   352.8  875.09   382.2  874.12   410.6  873.82   419.9   872.9   438.5  870.22
   457.2  866.22   465.4  865.12   466.5  864.97   475.8  865.26   480.4  866.02
   503.7  869.75     513  872.84   550.2  892.62     617  929.99   636.1  941.47
   683.9  971.95   693.5  977.52     770 1021.12   827.4 1053.31   865.7 1075.33
#Mann= 3 , 0 , 0
       0     .06       0   465.4    .045       0   480.4     .06       0
Bank Sta=465.4,480.4
XS Rating Curve= 0 ,0
Exp/Cntr=0.3,0.1

Type RM Length L Ch R = 1 ,31952.4 ,214.7,211.7,208.7
XS GIS Cut Line= 2
     1663843.536       310371.85     1664698.085      310354.551
#Sta/Elev= 30
       0 1047.05    49.1 1024.33      59 1019.35   176.8  954.45   245.6  917.32
   265.3  906.11   314.4  876.97   324.2  872.15     334  869.46   343.8  868.56
   402.8  866.56   442.1  864.51     444  864.65   451.9  865.24     459  866.83
   471.6  869.71   491.2  872.68     501  876.15   510.9  880.91   618.9  937.32
   628.8  942.75   668.1  965.48   677.9  970.32   707.4  983.28   746.7 1001.08
   756.5 1005.82   805.6  1032.1   835.1 1048.22   844.9  1053.3   854.7    1058
#Mann= 3 , 0 , 0
       0     .06       0     444    .045       0     459     .06       0
Bank Sta=444,459
XS Rating Curve= 0 ,0
Exp/Cntr=0.3,0.1