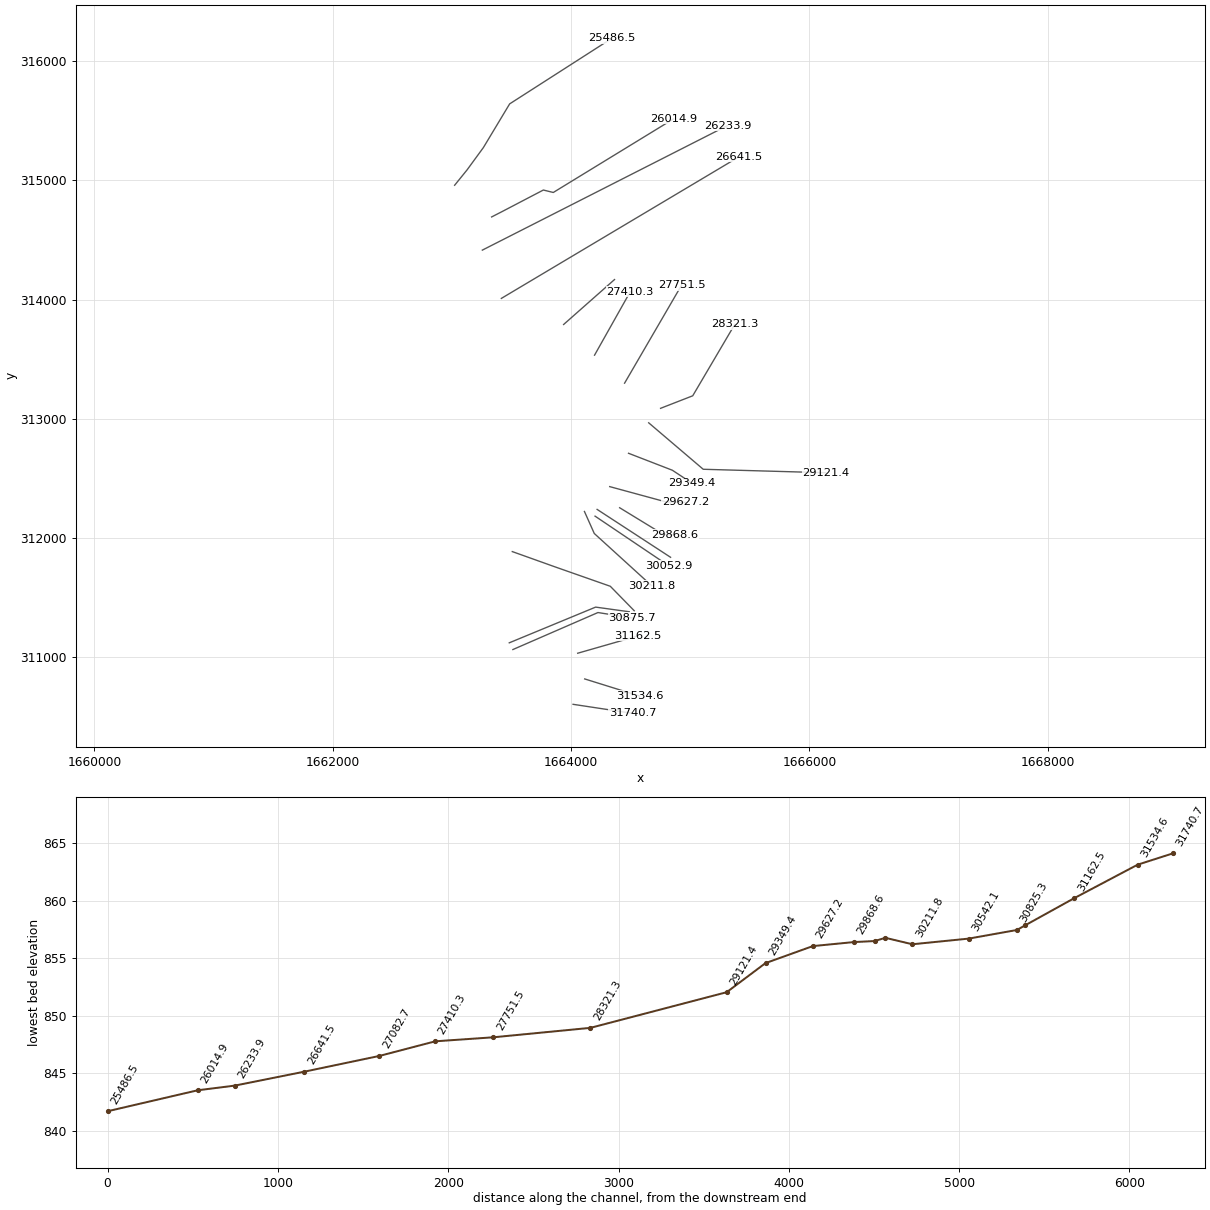
HEC-RAS study RBNSONFRK.prj: RBNSONFRK

--- RBNSONFRK.g01 (geometry) --- (continued)

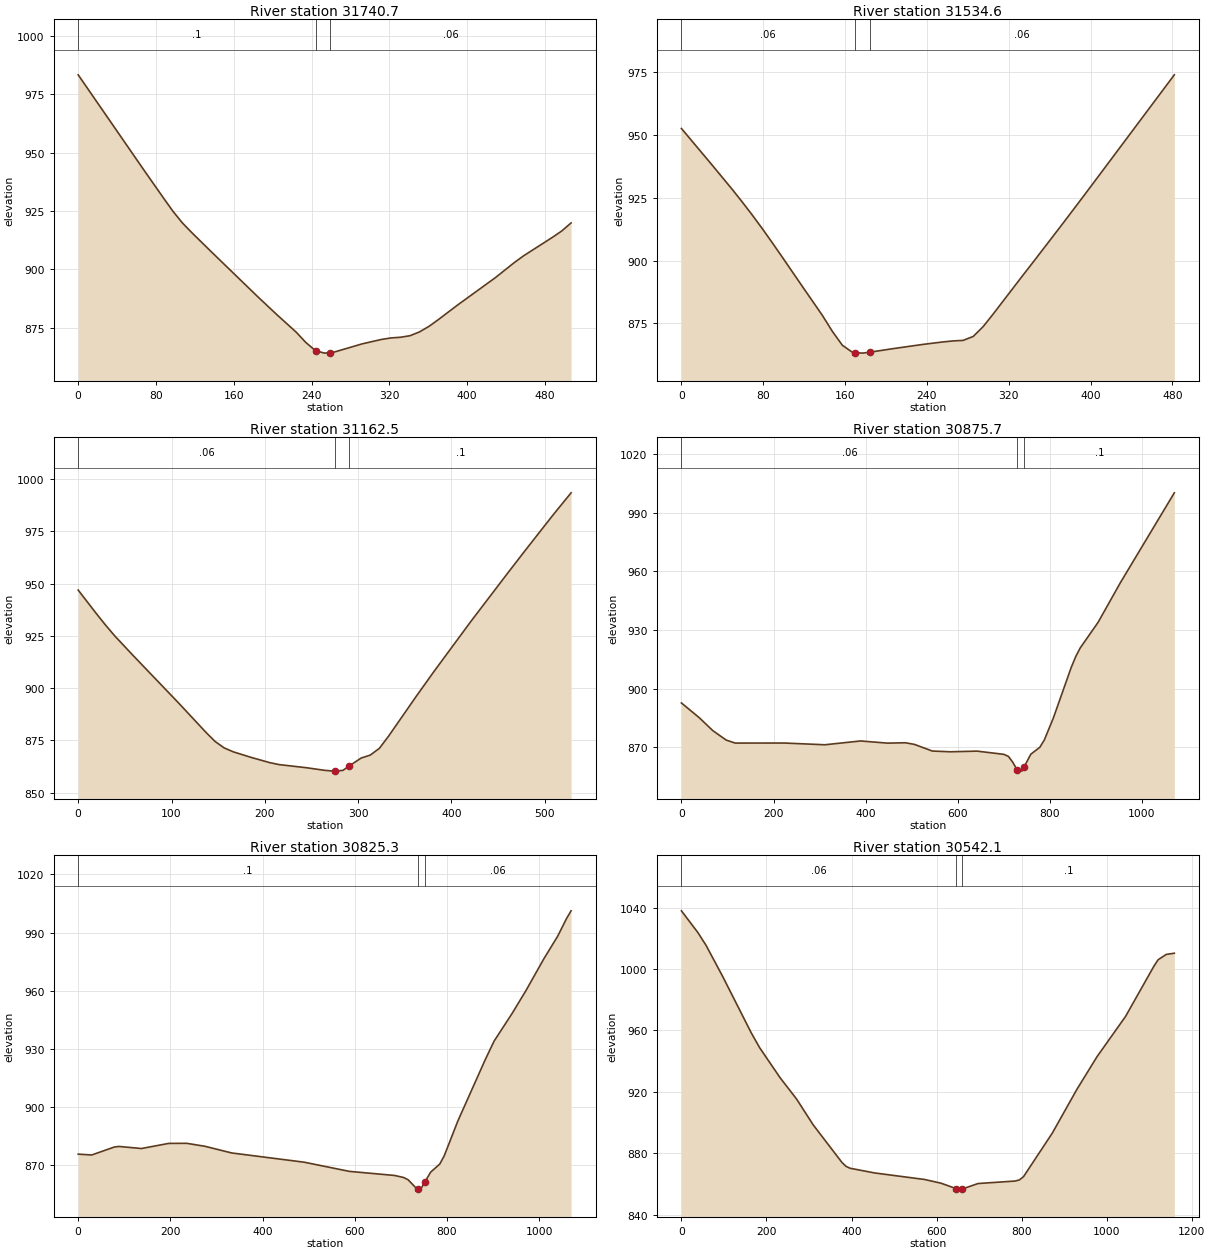
Type RM Length L Ch R = 1 ,31740.7 ,209.3,206.1,202.5
XS GIS Cut Line= 2
     1664016.356      310607.023     1664517.658      310531.068
#Sta/Elev= 30
       0  983.38    68.2  942.22    87.8  930.57    97.5  924.91   107.2  919.92
     117  915.71   136.5  907.74   185.3  888.07   204.8  880.45   224.3   873.1
     234  868.76   244.2  865.15   253.5  864.13   259.2  864.39   263.3  864.58
   292.5  868.14     312     870   321.8  870.64   331.5  870.93   341.3  871.59
     351  873.21   360.8  875.59   370.5   878.5     390  884.66     429  896.43
   448.5   902.9   458.3  905.87   487.5  913.66   497.3  916.44     507  919.92
#Mann= 3 , 0 , 0
       0      .1       0   244.2    .045       0   259.2     .06       0
Bank Sta=244.2,259.2
XS Rating Curve= 0 ,0
Exp/Cntr=0.3,0.1

Type RM Length L Ch R = 1 ,31534.6 ,358.8,372.1,385.2
XS GIS Cut Line= 2
     1664113.884      310819.828     1664573.953      310676.599
#Sta/Elev= 29
       0  952.64    29.5  938.32    49.2  928.61      59  923.59    68.8   918.4
    78.7  912.94    88.5  907.31    98.3  901.56     118  889.84   137.7  878.23
   147.5  871.84   157.3  866.29   167.2  863.46   169.3  863.39     177  863.15
   184.3  863.53   206.5  864.91     236  866.62   255.7  867.61   265.5  868.01
   275.3  868.22   285.2  869.78     295  873.74   304.8  878.76   334.3  894.43
   344.2  899.61   373.7  915.26   393.4  925.86   481.8  974.01
#Mann= 3 , 0 , 0
       0     .06       0   169.3    .045       0   184.3     .06       0
Bank Sta=169.3,184.3
XS Rating Curve= 0 ,0
Exp/Cntr=0.3,0.1

Type RM Length L Ch R = 1 ,31162.5 ,283.6,286.8,289.7
XS GIS Cut Line= 2
     1664055.026       311035.38     1664562.838      311180.779
#Sta/Elev= 30
       0  946.89    19.6  935.55    29.4   930.1    39.1     925    58.7  915.66
   107.6  892.85     137  878.77   146.7  874.44   156.5  871.34   166.3  869.46
   185.8  866.75   205.4  864.29   215.2  863.37   244.6  861.87   264.1  860.62
   273.9  860.24   275.7   860.3   283.7  860.59   290.7  862.79   303.2  866.49
     313  867.92   322.8  871.16   332.6  876.96   361.9   895.8   381.5  908.06
   420.6  931.75   459.8  954.72   479.3  965.99   508.6  982.66   528.2  993.42
#Mann= 3 , 0 , 0
       0     .06       0   275.7    .045       0   290.7      .1       0
Bank Sta=275.7,290.7
XS Rating Curve= 0 ,0
Exp/Cntr=0.3,0.1

Type RM Length L Ch R = 1 ,30875.7 ,50.8,50.4,50
XS GIS Cut Line= 3
     1663511.189      311066.196     1664225.164      311376.526
     1664513.793      311330.953
#Sta/Elev= 30
       0  892.76    38.9  885.19    68.1  878.62    97.3  873.77   116.8  872.24
   223.8  872.26   311.4  871.37   389.2  873.32   447.6  872.21   486.6   872.4
     506  871.57     545  868.17   583.9  867.78   642.3  868.12   700.6  866.47
   710.4  865.41   720.1  862.31   729.6  858.34   739.6  857.89   744.6  860.15
     759  866.56   778.5  870.08   788.2  873.78   807.7  884.92   846.7   910.9
   856.4  916.42   866.2  920.87   905.1     934   953.8  954.39  1070.7 1000.24
#Mann= 3 , 0 , 0
       0     .06       0   729.6    .045       0   744.6      .1       0
Bank Sta=729.6,744.6
XS Rating Curve= 0 ,0
Exp/Cntr=0.3,0.1

Type RM Length L Ch R = 1 ,30825.3 ,300,283.2,266
XS GIS Cut Line= 3
     1663480.807       311122.62     1664205.633      311422.099
     1664487.751      311383.036
#Sta/Elev= 30
       0  875.54    29.4  875.11    78.4  879.21    88.2  879.52   137.2  878.44
   196.1  881.08   235.3  881.13   274.5  879.62   333.3  876.14   490.2  871.38
   588.2  866.64   686.2  864.53   705.8  863.49   715.6  862.32   735.2  857.47
   736.3  857.56     745  858.26   751.3  860.93   764.6  866.27   784.3  870.42
   794.1  874.75   823.5  892.67   882.5  924.11   902.1  933.91   941.4  948.29
   970.9  959.89  1010.1  976.46  1039.6  987.91  1059.2   997.2  1069.1 1001.21
#Mann= 3 , 0 , 0
       0      .1       0   736.3    .045       0   751.3     .06       0
Bank Sta=736.3,751.3
XS Rating Curve= 0 ,0
Exp/Cntr=0.3,0.1

Type RM Length L Ch R = 1 ,30542.1 ,339.7,330.3,320.5
XS GIS Cut Line= 4
     1663506.245      311887.537     1663870.828      311757.328
     1664328.727      311596.738     1664529.299      311391.815
#Sta/Elev= 30
       0 1037.88    38.7 1023.74    58.1 1015.34    96.8  995.27   164.5   958.3
   183.9  948.81   232.3  929.13     271   915.3   309.7  898.62   377.5  874.09
   387.1  871.56   396.8  870.29   455.1  867.22   571.5  863.01   610.4  860.59
   645.6  857.09   658.9  856.72   660.6  856.83   697.7  860.37     785  861.99
   794.7   862.7   804.4  864.81   872.4   893.3   929.7  921.53   977.5  943.01
  1044.4  969.14  1111.3 1001.93  1120.9    1006    1140  1009.5  1159.1 1010.28
#Mann= 3 , 0 , 0
       0     .06       0   645.6    .045       0   660.6      .1       0
Bank Sta=645.6,660.6
XS Rating Curve= 0 ,0
Exp/Cntr=0.3,0.1

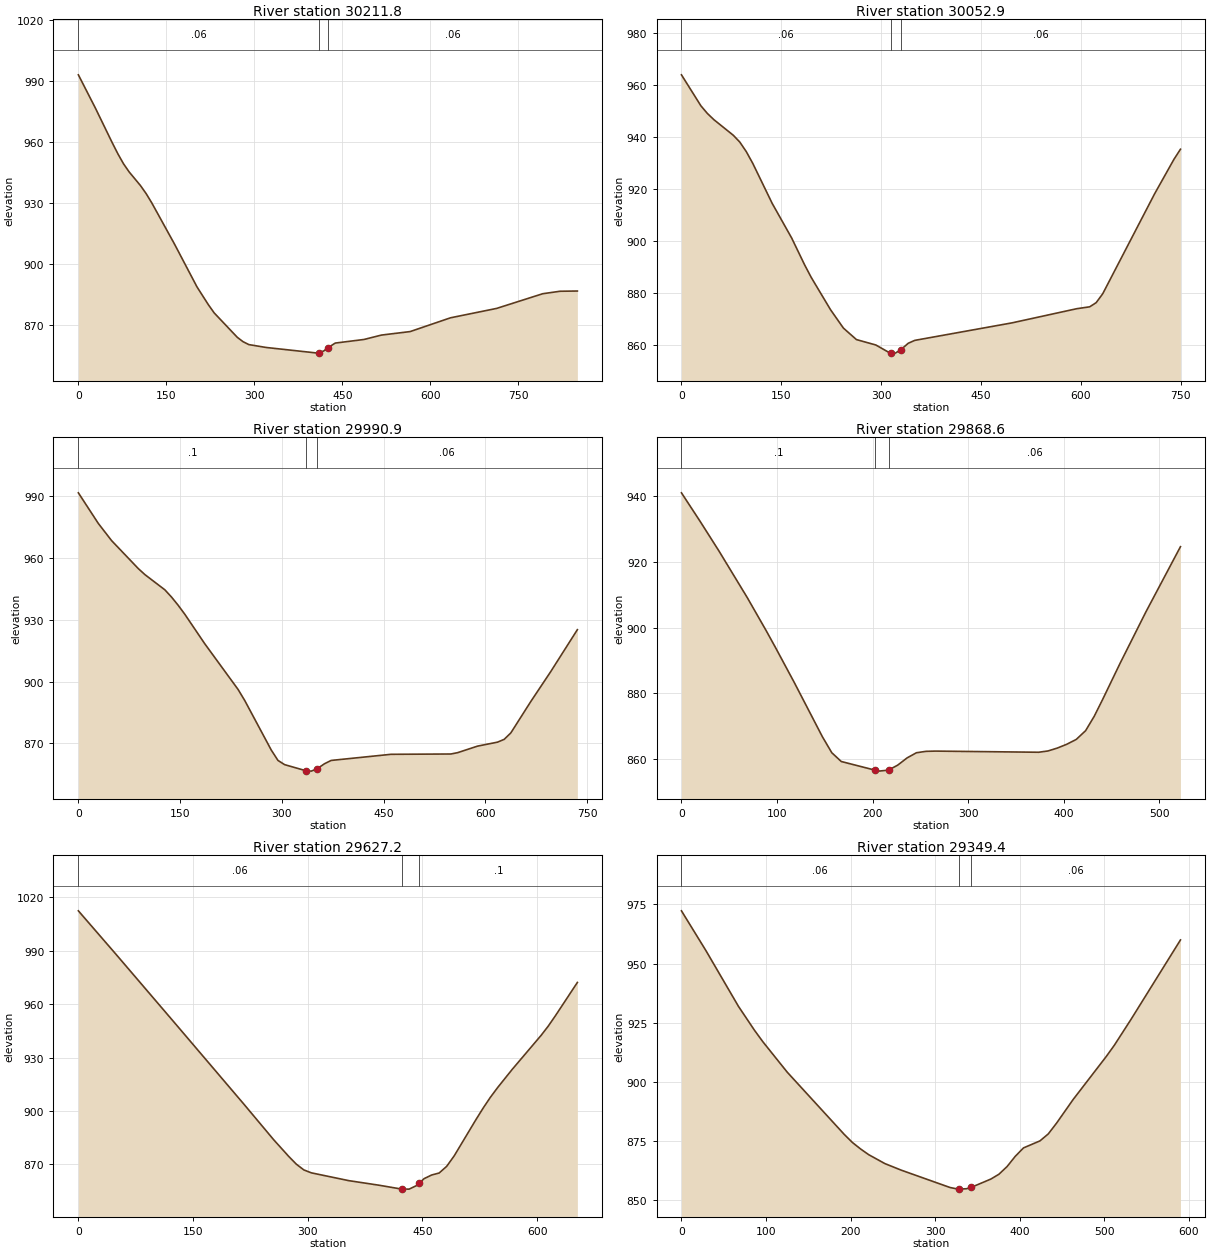
Type RM Length L Ch R = 1 ,30211.8 ,155.7,159,162.3
XS GIS Cut Line= 3
     1664111.714      312223.908     1664194.179      312039.446
     1664673.779      311603.249
#Sta/Elev= 30
       0  992.92    28.9  976.65    57.7  959.59    67.4  954.09      77   949.2
    86.6  945.21   105.8  938.54   115.5  934.58   125.1  930.03   163.6  909.92
   202.1  888.79   221.7  879.95   231.5  875.97   270.8  864.01   280.6  861.86
   290.5  860.42   319.9  859.01   408.3  856.23   410.9  856.51   418.2   857.3
   425.9  858.99   437.8  861.17   486.9  862.94   516.4  865.09   565.5  866.82
   634.2  873.58   712.8  878.19   791.4  885.41   820.9  886.62   850.4  886.73
#Mann= 3 , 0 , 0
       0     .06       0   410.9    .045       0   425.9     .06       0
Bank Sta=410.9,425.9
XS Rating Curve= 0 ,0
Exp/Cntr=0.3,0.1

Type RM Length L Ch R = 1 ,30052.9 ,61.6,61.9,62.2
XS GIS Cut Line= 2
     1664200.774      312184.761     1664822.471      311766.208
#Sta/Elev= 30
       0  963.99    29.2  952.06    38.9  949.12    48.7  946.72    77.9   940.7
    87.6   938.1    97.3  934.43   107.1  929.89   136.3  914.46   165.5  901.15
   184.9  890.84   194.7  886.05   223.9  873.52   243.3  866.42   262.8  862.01
     292  859.92   311.5  857.08   314.2     857   321.2  856.79   329.2  858.05
   340.7   860.6   350.4   861.7   496.4  868.44   593.7   873.9   613.2  874.63
   622.9  876.23   632.7  879.64   710.5  918.08   739.7  931.44   749.5  935.33
#Mann= 3 , 0 , 0
       0     .06       0   314.2    .045       0   329.2     .06       0
Bank Sta=314.2,329.2
XS Rating Curve= 0 ,0
Exp/Cntr=0.3,0.1

Type RM Length L Ch R = 1 ,29990.9 ,121.7,122.4,123.1
XS GIS Cut Line= 2
      1664218.05      312241.269      1664834.37      311839.794
#Sta/Elev= 30
       0  991.57    29.4  976.72      49  968.37    88.3  954.82    98.1  951.88
   127.5   944.5   137.3  940.99   147.1  937.01   156.9  932.65   186.3  918.34
   235.4  896.17   245.2  890.82   284.4  866.72   294.2  861.72     304  859.66
   336.1  856.63   343.3  856.51   351.1  857.49   362.9   860.1   372.7   861.7
   460.9  864.67   549.2  864.82     559  865.46   588.4  868.64   617.9  870.57
   627.7  871.93   637.5  875.05   666.9  890.27   696.3  904.79   735.6  925.16
#Mann= 3 , 0 , 0
       0      .1       0   336.1    .045       0   351.1     .06       0
Bank Sta=336.1,351.1
XS Rating Curve= 0 ,0
Exp/Cntr=0.3,0.1

Type RM Length L Ch R = 1 ,29868.6 ,234.8,241.4,247.9
XS GIS Cut Line= 3
     1664407.113      312255.245     1664768.224      312034.759
     1664867.182      312026.078
#Sta/Elev= 30
       0   940.9    19.7  932.17    39.4  923.18    68.9  909.09    88.6  899.11
    98.4  893.96   118.1  883.33   147.6  866.83   157.4     862   167.3  859.34
   202.7  856.71   206.6  856.42   216.5  856.72   217.7   856.9   226.3  858.22
   236.2  860.43     246     862   255.8  862.42   265.7   862.5   373.9  862.15
   383.7  862.54   393.6  863.43   403.4  864.58   413.3  866.04   423.1   868.7
   432.1  873.06   441.2  878.34   459.2  889.16   486.3   904.8   522.4  924.55
#Mann= 3 , 0 , 0
       0      .1       0   202.7    .045       0   217.7     .06       0
Bank Sta=202.7,217.7
XS Rating Curve= 0 ,0
Exp/Cntr=0.3,0.1

Type RM Length L Ch R = 1 ,29627.2 ,280.3,277.8,275.3
XS GIS Cut Line= 3
     1664323.779      312432.328     1664798.122      312303.385
     1664959.196      312300.384
#Sta/Elev= 30
       0 1012.39    49.2  987.99   127.8  948.53   216.3   903.9   255.6  883.75
   275.3  874.38   285.1  870.09   294.9  866.86   304.8  865.21   353.9  860.82
   393.2  858.27   422.7   856.1   431.1  856.07   432.6  856.07   442.4  858.07
   446.1  859.53   452.2  861.95   462.1     864   471.9  865.12   481.7  868.84
   491.6  874.76     520  895.08   529.5  901.62   538.9  907.64   548.4  913.11
   567.4  923.29   605.3  942.45   614.8  947.74   624.2   953.6   652.7  972.16
#Mann= 3 , 0 , 0
       0     .06       0   422.7    .045       0   446.1      .1       0
Bank Sta=422.7,446.1
XS Rating Curve= 0 ,0
Exp/Cntr=0.3,0.1

Type RM Length L Ch R = 1 ,29349.4 ,235.6,228,220.3
XS GIS Cut Line= 3
     1664481.766      312711.842     1664849.821      312569.481
     1665012.968      312461.991
#Sta/Elev= 30
       0  972.32    28.9  955.51    67.4  931.91    86.6  921.66    96.2  916.96
   125.1  904.05   192.5  877.73   202.1  874.33   211.8  871.58   221.4  869.16
   240.6  865.38   259.9  862.61   317.6  855.27   327.2  854.59   327.6   854.6
   336.9  854.75   342.6  855.34   365.8  858.84   375.4   860.9     385  864.14
   394.6  868.43   404.4  872.03   423.9     875   433.7  877.94   443.5   882.5
     463  892.45   502.1  910.62   511.8  915.45   531.4  926.32     590     960
#Mann= 3 , 0 , 0
       0     .06       0   327.6    .045       0   342.6     .06       0
Bank Sta=327.6,342.6
XS Rating Curve= 0 ,0
Exp/Cntr=0.3,0.1

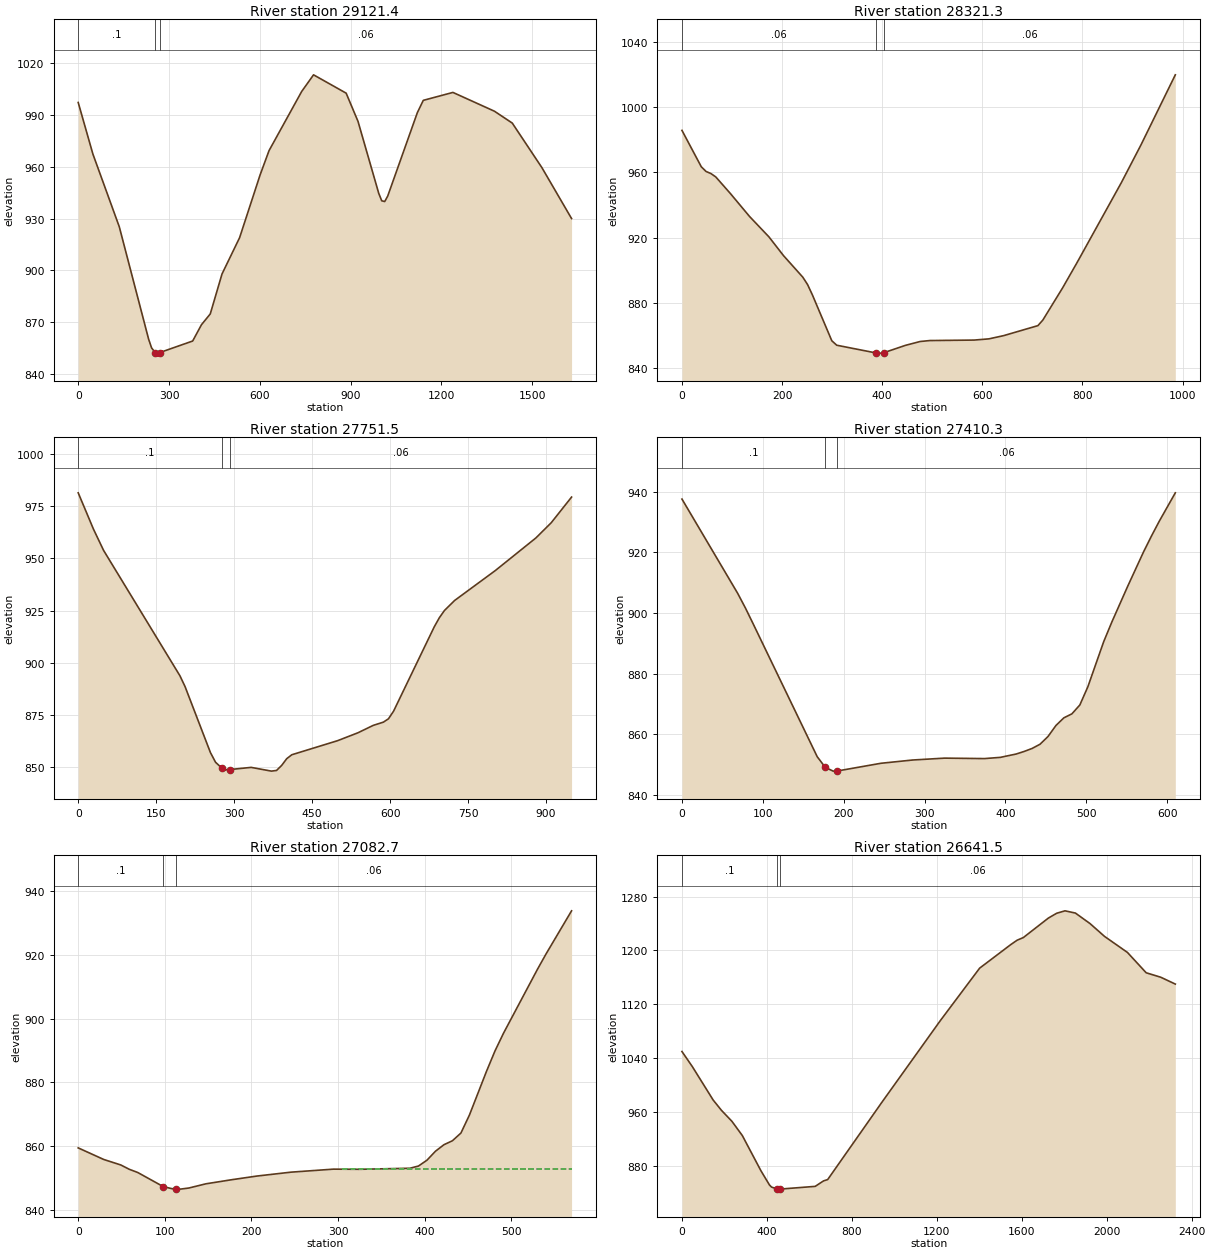
Type RM Length L Ch R = 1 ,29121.4 ,759.6,800.1,840
XS GIS Cut Line= 3
     1664650.827      312967.336     1665108.537      312577.795
     1666136.795      312548.651
#Sta/Elev= 30
       0  997.23    48.5  967.37   135.7  925.24   232.7  860.09   242.4  855.08
   254.8   852.3   261.7  852.06   269.8  852.41   378.1  859.07   407.2  868.52
   436.2  874.75     475  897.89   533.2  918.96     601  955.36   630.4  969.35
   738.2 1003.61   777.4 1013.25   885.1 1002.63   924.3  986.27   992.9  944.53
  1002.7  940.28  1012.5  939.86  1022.3  942.98  1120.3  991.35  1139.9  998.46
  1237.8 1003.06    1375  992.17  1433.8  985.31  1531.7   959.5  1629.7  930.01
#Mann= 3 , 0 , 0
       0      .1       0   254.8    .045       0   269.8     .06       0
Bank Sta=254.8,269.8
XS Rating Curve= 0 ,0
Exp/Cntr=0.3,0.1

Type RM Length L Ch R = 1 ,28321.3 ,569.3,569.8,570.2
XS GIS Cut Line= 3
     1664750.654      313088.863     1665020.441      313193.894
     1665373.696      313793.401
#Sta/Elev= 30
       0  985.86    38.6   963.5    48.2   960.6    57.9  959.31    67.6  957.23
    96.5  947.13   135.1  932.91   173.7  920.42   202.7  908.93   241.3  895.66
   250.9   891.1   260.6   884.7   299.3  856.56   309.1  853.82   388.1  849.04
   397.3  848.96   403.1  849.22   446.3  853.73   475.7   856.1   495.3  856.69
   583.5  856.98   612.9  857.72   642.3  859.69   710.9  865.85   720.7  869.23
   759.9  888.86   789.3  904.69   877.6  953.73   916.8  976.93   985.4    1020
#Mann= 3 , 0 , 0
       0     .06       0   388.1    .045       0   403.1     .06       0
Bank Sta=388.1,403.1
XS Rating Curve= 0 ,0
Exp/Cntr=0.3,0.1

Type RM Length L Ch R = 1 ,27751.5 ,340.8,341.2,341.4
XS GIS Cut Line= 2
      1664448.57      313299.801     1664926.001      314120.113
#Sta/Elev= 30
       0  981.42    29.4     964    48.9  953.82   195.7   893.8   205.5  888.66
   254.4  857.01   264.2  852.39     277  849.43   283.8  848.74     292   848.9
   332.7  849.93   371.8  848.14   381.6  848.47   391.4  850.88   401.2  854.11
     411  855.99     499  862.72   538.2  866.51   567.5  870.04   587.1   871.6
   596.9  873.21   606.7  876.86   684.9  917.22   694.7  921.57   704.5  925.05
   724.1  929.86   802.4  944.19   880.6  959.84     910   967.1   949.1  979.38
#Mann= 3 , 0 , 0
       0      .1       0     277    .045       0     292     .06       0
Bank Sta=277,292
XS Rating Curve= 0 ,0
Exp/Cntr=0.3,0.1

Type RM Length L Ch R = 1 ,27410.3 ,334.1,327.7,319.8
XS GIS Cut Line= 2
     1664196.477      313534.541     1664495.957      314066.225
#Sta/Elev= 30
       0   937.6    68.9  906.49    78.7  901.53    88.6  896.12   167.3  852.55
   177.2  849.06     187  847.79   192.2  847.84   246.1  850.38   285.4  851.46
   324.8  852.08     374  851.93   393.7  852.33   413.4  853.44   423.2  854.28
   433.1  855.28   442.9  856.67   452.8  859.24   462.6  862.87   472.4  865.39
   482.3   866.7   492.1  869.62     502  875.62   521.6  890.51   531.5  896.89
   551.2  908.75   570.9  920.16   580.7   925.4   590.5  930.36   610.2  939.66
#Mann= 3 , 0 , 0
       0      .1       0   177.2    .045       0   192.2     .06       0
Bank Sta=177.2,192.2
XS Rating Curve= 0 ,0
Exp/Cntr=0.3,0.1

Type RM Length L Ch R = 1 ,27082.7 ,445.2,441.1,436.6
XS GIS Cut Line= 2
     1663936.974      313791.703     1664364.057       314168.44
#Sta/Elev= 30
       0  859.46    29.5  855.82    49.1  854.11    58.9  852.75    68.7  851.74
      98  847.34     108  846.67     113  846.59   117.8  846.52   127.6  846.86
   147.3  848.18   176.7  849.45   206.2  850.62   245.5  851.84   294.6  852.79
     324  852.74   382.9  853.07   392.8  853.77   402.6   855.6   412.4  858.41
   422.2  860.46     432   861.7   441.8  864.12   451.7  869.83   471.3  883.48
   481.1  889.87     491  895.47   530.2  915.53     540  920.29   569.5  933.84
#Mann= 3 , 0 , 0
       0      .1       0      98    .045       0     113     .06       0
#XS Ineff= 2 , 0
                          304.24          852.91
Permanent Ineff=
       F       F
Bank Sta=98,113
XS Rating Curve= 0 ,0
Exp/Cntr=0.3,0.1

Type RM Length L Ch R = 1 ,26641.5 ,409,407.7,406.5
XS GIS Cut Line= 2
     1663414.404      314010.453     1665410.379      315198.561
#Sta/Elev= 30
       0 1049.74      49 1027.25     147   977.6   186.2  962.22   235.2  945.98
   284.2  924.82   372.4  872.15   411.6  851.55   421.4  848.28   445.4  845.57
   460.4  845.15   627.3  849.26   666.5  857.36   686.1  859.35   940.9   974.1
  1215.3  1095.2  1401.5 1173.67  1548.6 1208.83    1578 1215.22  1607.4  1219.2
    1725 1248.11  1764.2  1255.3  1803.4 1258.92  1852.4 1255.59    1921 1240.02
  1989.6 1220.89  2097.4 1197.06  2185.6 1166.83  2254.2 1160.19  2322.8    1150
#Mann= 3 , 0 , 0
       0      .1       0   445.4    .045       0   460.4     .06       0
Bank Sta=445.4,460.4
XS Rating Curve= 0 ,0
Exp/Cntr=0.3,0.1

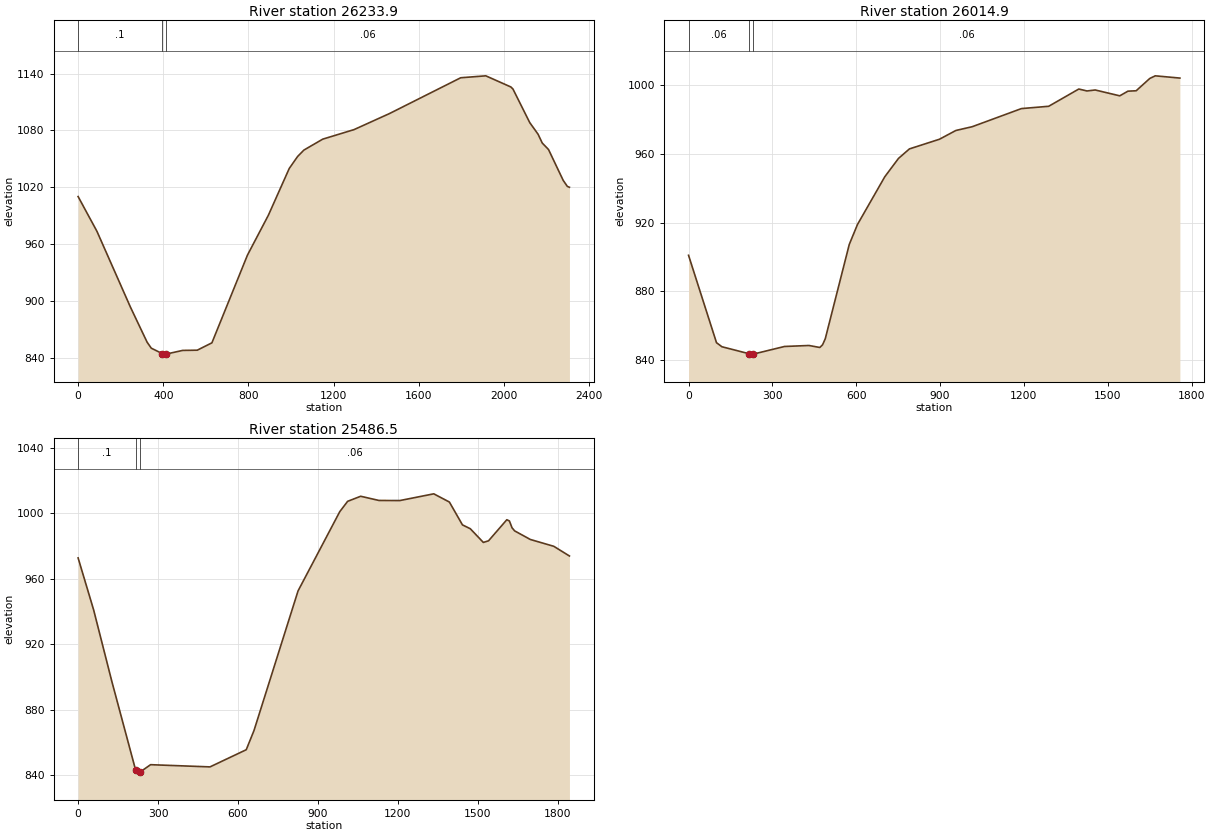
Type RM Length L Ch R = 1 ,26233.9 ,219.1,219,218.6
XS GIS Cut Line= 2
     1663254.816      314415.248     1665311.955      315459.747
#Sta/Elev= 30
       0  1010.2    88.4  973.54   245.4  893.71     324  856.53   343.6  850.22
   395.5  844.47   410.5  843.95   412.3  843.94   490.9  847.86   559.6  848.09
   628.3  855.86   795.2  948.41   893.4  990.46   991.6  1039.9  1030.8 1052.49
  1060.3 1059.23  1148.6 1070.75  1295.9 1080.84  1462.8 1097.83  1796.6 1135.53
  1914.4 1137.57  2032.2 1125.81    2042 1123.61  2120.6 1088.26  2159.9 1075.94
  2179.5 1066.64  2208.9 1059.82  2277.7 1027.31  2297.3  1020.9  2307.1    1020
#Mann= 3 , 0 , 0
       0      .1       0   395.5    .045       0   410.5     .06       0
Bank Sta=395.5,410.5
XS Rating Curve= 0 ,0
Exp/Cntr=0.3,0.1

Type RM Length L Ch R = 1 ,26014.9 ,517.2,528.4,539.1
XS GIS Cut Line= 5
     1663332.762      314693.395     1663421.738      314738.968
      1663766.79      314919.089     1663850.198      314898.603
     1664859.435      315515.575
#Sta/Elev= 30
       0  901.08     100  850.19   119.4  847.83   216.8  843.75   226.5  843.53
   231.8  843.55   343.2  847.98   430.8  848.56   469.7   847.4   479.5  848.96
   489.2  852.49   575.1  907.42   604.4  919.01   702.2  946.83   751.1  957.48
   790.2  963.03   897.7  968.66   956.4  973.76    1015  975.96    1191  986.51
  1288.7  987.86  1396.3   997.9  1425.6  996.77  1454.9  997.35  1542.9  993.94
  1572.2  996.66  1601.6  996.89  1650.4 1004.07    1670 1005.59    1758 1004.28
#Mann= 3 , 0 , 0
       0     .06       0   216.8    .045       0   231.8     .06       0
Bank Sta=216.8,231.8
XS Rating Curve= 0 ,0
Exp/Cntr=0.3,0.1

Type RM Length L Ch R = 1 ,25486.5 ,192.1,195.3,195.4
XS GIS Cut Line= 5
     1663022.304      314959.151      1663126.47      315087.624
     1663263.623      315275.124     1663484.109      315641.443
     1664341.488      316191.009
#Sta/Elev= 30
       0  972.71    58.4  940.84   126.5  897.23   213.8   844.2   218.6  842.97
   223.5  841.71   233.6  841.87   271.9  846.26   494.9  844.91   630.9   855.4
   660.1   867.2   825.3  952.53   981.9    1001  1011.3  1007.3  1060.3  1010.4
  1128.8 1007.83  1207.2 1007.77  1334.5 1011.89  1393.2 1006.86  1442.2   992.9
  1471.6  990.55  1520.5  982.17  1540.1  983.17  1608.6  996.04  1618.4  995.29
  1628.2  991.11    1638  989.23  1696.8  983.98  1784.9   979.8  1843.6  973.88
#Mann= 3 , 0 , 0
       0      .1       0   218.6    .045       0   233.6     .06       0
Bank Sta=218.6,233.6
XS Rating Curve= 0 ,0
Exp/Cntr=0.3,0.1