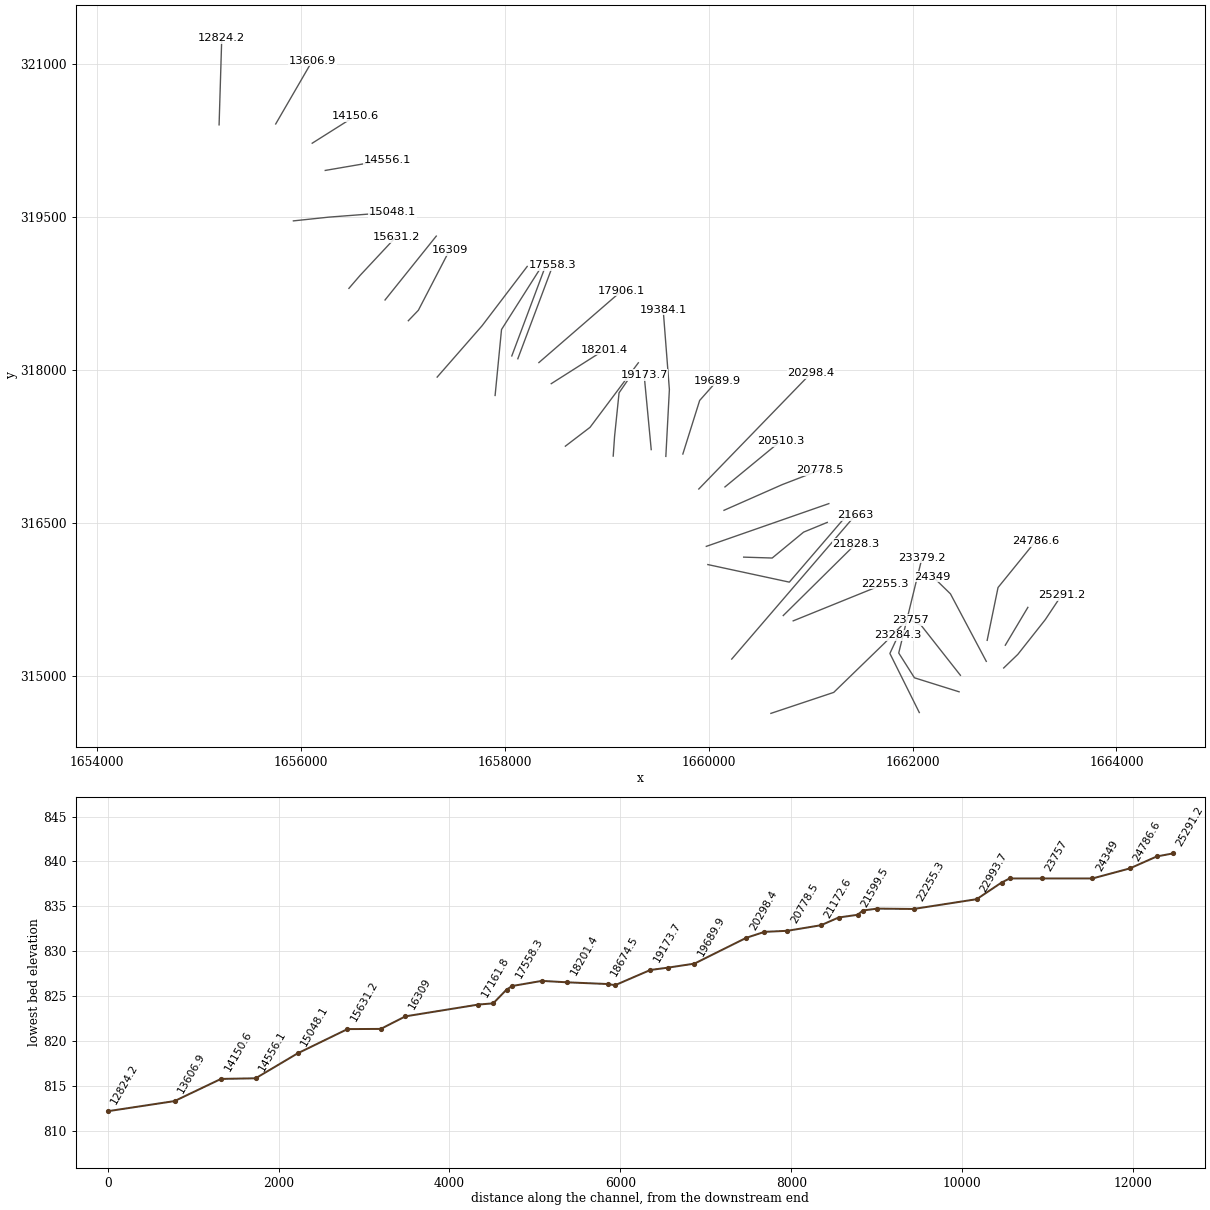
HEC-RAS study RBNSONFRK.prj: RBNSONFRK

--- RBNSONFRK.g01 (geometry) --- (continued)

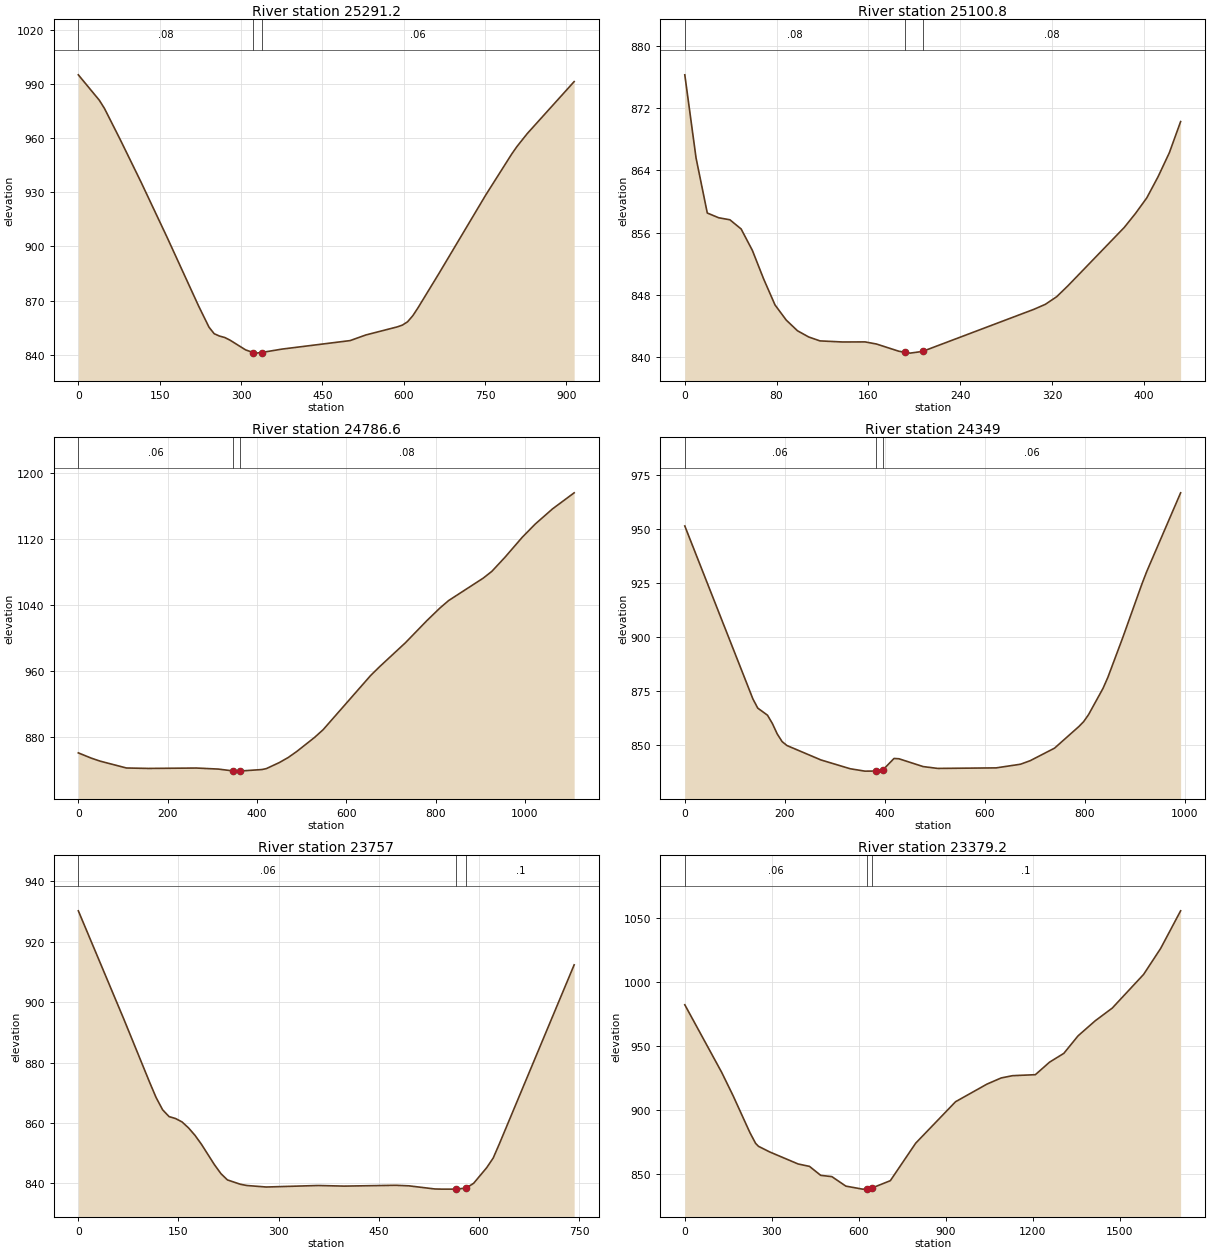
Type RM Length L Ch R = 1 ,25291.2 ,191.2,190.4,191.8
XS GIS Cut Line= 4
     1662893.832      315075.471      1663032.72      315209.151
     1663301.818      315549.429      1663461.54      315789.012
#Sta/Elev= 30
       0  994.99    38.6  980.96    48.2  976.39    77.1  959.24   115.7  935.56
   163.9   904.9   221.7  867.07     241  855.27   250.6  851.63   260.2  850.35
   269.9  849.56   279.5  848.13   308.5  842.69   322.9  841.16   327.7  840.89
   337.9  841.23   375.9  843.13   501.3  847.83   530.2  850.94     588   855.4
   597.7  856.41   607.3  858.26     617  861.64   626.6  866.04     665  884.93
   751.4  928.43   799.4  951.16     809  955.29   828.2  962.52   914.5  991.24
#Mann= 3 , 0 , 0
       0     .08       0   322.9    .045       0   337.9     .06       0
Bank Sta=322.9,337.9
XS Rating Curve= 0 ,0
Exp/Cntr=0.3,0.1

Type RM Length L Ch R = 1 ,25100.8 ,305.4,314.3,321.7
XS GIS Cut Line= 2
     1662909.585      315298.864     1663130.939      315669.957
#Sta/Elev= 30
       0  876.26     9.8   865.6    19.6  858.53    29.5  857.92    39.3  857.66
    49.1  856.48    58.9  853.73    68.7  850.07    78.6  846.74    88.4  844.79
    98.2  843.42     108  842.62   117.8  842.12   137.5  841.98   157.1  841.99
     167  841.72   186.6  840.79   192.2  840.65   196.4  840.55   207.2  840.77
   304.4  846.18   314.2  846.81   324.1  847.79   333.9  849.19     383  856.68
   392.8  858.48   402.6  860.47   412.5   863.2   422.3  866.27   432.1  870.26
#Mann= 3 , 0 , 0
       0     .08       0   192.2    .045       0   207.2     .08       0
Bank Sta=192.2,207.2
XS Rating Curve= 0 ,0
Exp/Cntr=0.3,0.1

Type RM Length L Ch R = 1 ,24786.6 ,423.3,437.6,452.7
XS GIS Cut Line= 3
     1662731.634      315346.607     1662838.276      315864.533
     1663205.005       316315.97
#Sta/Elev= 30
       0  861.32    29.4  854.88      49  851.29   107.7  843.02   156.7  842.49
   264.4  842.96   313.4  841.71     346  839.49   352.5  839.22     361  839.29
   411.3  841.14   421.1  842.28   450.4  849.67     470  855.71   489.6  863.18
   528.8  879.94   548.2  889.39   654.8  955.18   674.2  965.48   732.4  994.68
   780.8 1021.68   809.9 1036.87   829.3 1045.88   906.8 1073.04   926.2 1081.32
   955.3 1098.22   994.1 1122.51  1023.2 1138.54    1062 1156.96  1110.4 1176.39
#Mann= 3 , 0 , 0
       0     .06       0     346    .045       0     361     .08       0
Bank Sta=346,361
XS Rating Curve= 0 ,0
Exp/Cntr=0.3,0.1

Type RM Length L Ch R = 1 ,24349   ,587.3,592,596.5
XS GIS Cut Line= 3
     1662722.953      315140.443     1662371.391      315802.336
     1662197.779      315971.607
#Sta/Elev= 30
       0  951.48   136.3  871.46     146  867.23   165.5  863.95   175.2  860.12
   184.9   855.3   194.7  851.75   204.4  849.93   272.5  843.26   330.9   839.2
   360.1   838.1   381.9  838.12   396.9   838.8   418.5  843.95   428.3  843.82
   476.9   840.2   506.1  839.35   622.9   839.6   671.6  841.29   691.1  842.94
   739.7  848.73   788.3  858.71     798  861.02   807.7  864.22   836.8  876.45
   846.4   881.5   875.6  899.51   914.4   924.6     924  930.36   991.9  966.81
#Mann= 3 , 0 , 0
       0     .06       0   381.9    .045       0   396.9     .06       0
Bank Sta=381.9,396.9
XS Rating Curve= 0 ,0
Exp/Cntr=0.3,0.1

Type RM Length L Ch R = 1 ,23757   ,380.6,377.8,374.4
XS GIS Cut Line= 3
     1662469.047      315003.725     1662084.932      315492.006
     1661976.425      315546.259
#Sta/Elev= 30
       0  930.27      68  894.48   106.8  873.47   116.5  868.43   126.2  864.39
   135.9  862.12   145.6  861.48   155.3  860.36     165  858.39   174.7  855.92
   184.4  852.95   203.8  846.21   213.6  843.22   223.3  841.15   242.7  839.71
   252.4   839.3   281.5   838.8   359.2   839.3     398   839.1   475.6  839.37
   495.1  839.19   533.9  838.15   543.6   838.1   566.2   838.1   581.2  838.46
   592.1  840.05   611.6   845.2   621.3  848.38   630.6  853.11   742.6  912.38
#Mann= 3 , 0 , 0
       0     .06       0   566.2    .045       0   581.2      .1       0
Bank Sta=566.2,581.2
XS Rating Curve= 0 ,0
Exp/Cntr=0.3,0.1

Type RM Length L Ch R = 1 ,23379.2 ,96.8,94.8,93.6
XS GIS Cut Line= 4
     1662456.176       314841.76     1662017.964      314979.117
     1661863.884      315222.172     1662092.779      316157.147
#Sta/Elev= 30
       0  982.27     127  929.49   166.1  911.36   224.7  882.22   244.3  873.84
     254   871.6   293.1  867.14   390.8  857.76   429.9  855.89   468.8  848.86
   507.2  847.87   555.2  840.46   612.7   838.1   629.7  838.12   644.7  838.93
   708.6  844.69   796.1  874.02   933.6  906.45  1041.7   920.2  1090.8  925.03
  1130.1  926.81  1208.7  927.59  1257.8   937.4  1306.9  944.26    1356  957.97
  1414.9  969.69  1473.9  979.67  1581.9 1005.98  1640.8 1026.34  1709.6 1055.72
#Mann= 3 , 0 , 0
       0     .06       0   629.7    .045       0   644.7      .1       0
Bank Sta=629.7,644.7
XS Rating Curve= 0 ,0
Exp/Cntr=0.3,0.1

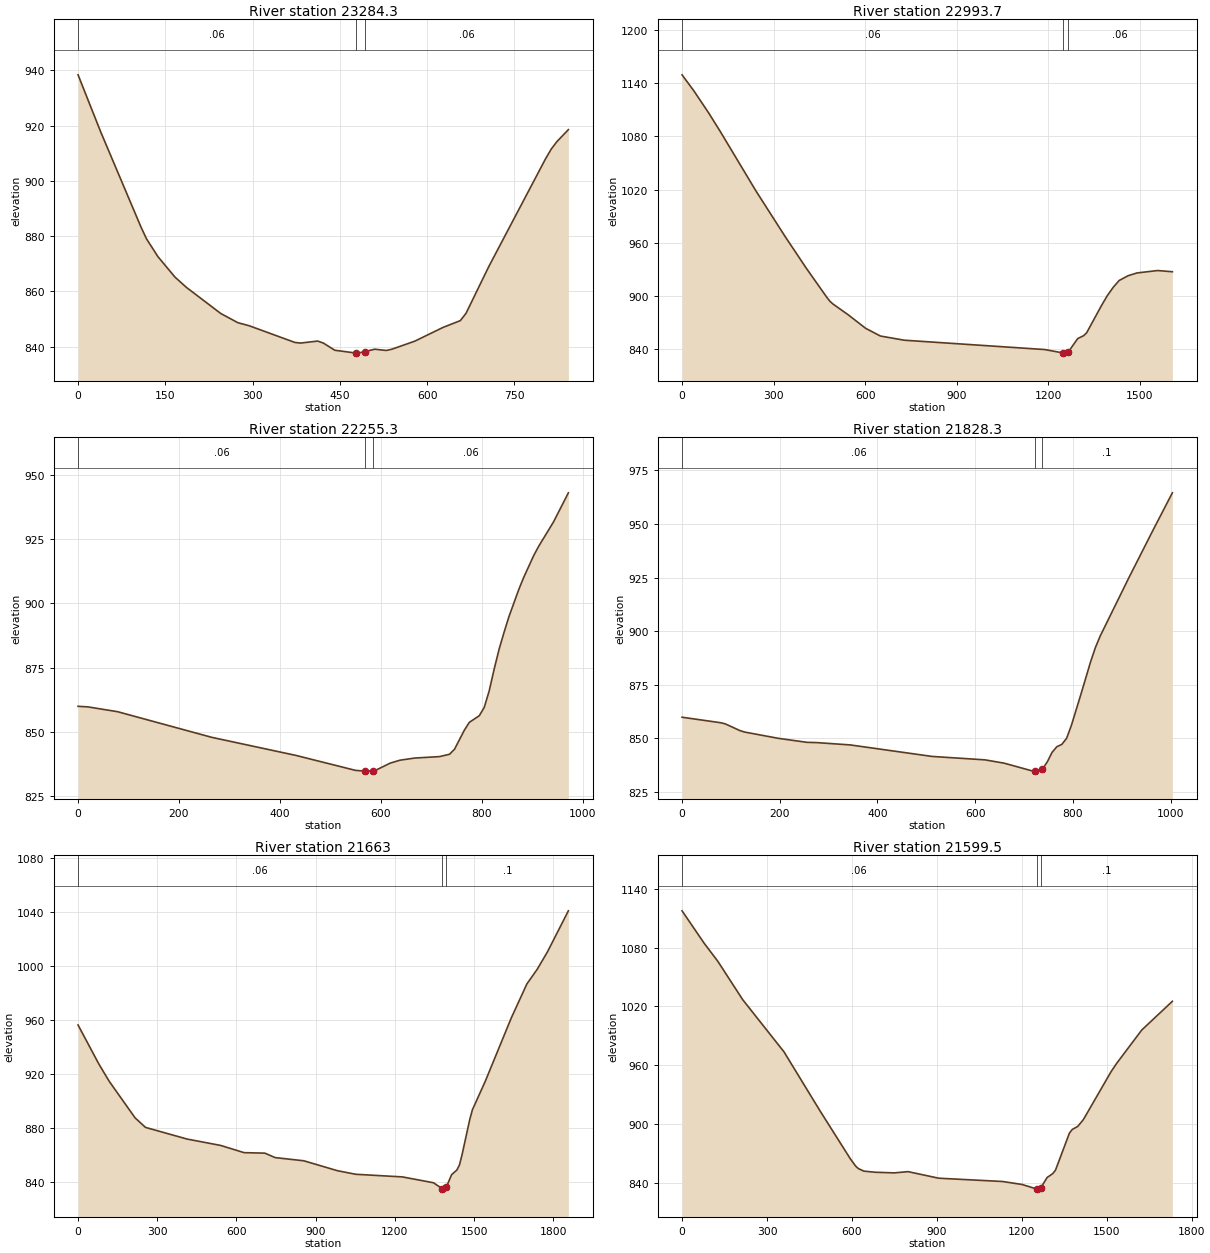
Type RM Length L Ch R = 1 ,23284.3 ,319.6,290.6,261.1
XS GIS Cut Line= 3
     1662065.707      314638.405     1661777.078      315217.832
     1661859.387      315395.146
#Sta/Elev= 30
       0  938.39    39.2   917.6   107.9  883.42   117.7     879   137.3  872.57
   166.7  865.14   186.4  861.42   245.2     852   274.6  848.67   294.2  847.55
   372.7  841.51   382.5  841.28   411.9  842.01   421.8  841.26   441.4  838.68
   478.2  837.65   480.6  837.64   493.2   838.2     510  839.06   529.6   838.6
   539.4  839.05   578.7  841.96   627.7  846.98   657.1  849.41   666.9  852.06
     706  868.97   803.7  908.04   813.5  911.55   823.3  914.26   842.8  918.54
#Mann= 3 , 0 , 0
       0     .06       0   478.2    .045       0   493.2     .06       0
Bank Sta=478.2,493.2
XS Rating Curve= 0 ,0
Exp/Cntr=0.3,0.1

Type RM Length L Ch R = 1 ,22993.7 ,748.3,738.4,726.7
XS GIS Cut Line= 4
     1660609.519      314630.206     1661225.863      314835.887
     1661724.995      315319.828     1661907.262      315506.942
#Sta/Elev= 30
       0 1149.24    38.8 1131.16    87.3 1106.26   126.1 1084.92   242.4 1018.28
   339.4  966.19   407.3   931.3   475.2  898.18   484.9  894.01   494.6  891.05
   543.1  879.28   601.3  863.76   649.8  855.04   728.1  850.34  1188.3  839.81
  1248.2  835.99  1256.8  835.79  1263.2  837.07  1266.6  837.75    1296  852.14
  1315.6  855.45  1325.4  858.72    1374  889.38  1393.4  900.71  1412.7  910.03
    1432  917.62  1461.1  922.94  1490.1  926.09  1557.8  928.82  1606.2  927.45
#Mann= 3 , 0 , 0
       0     .06       0  1248.2    .045       0  1263.2     .06       0
Bank Sta=1248.2,1263.2
XS Rating Curve= 0 ,0
Exp/Cntr=0.3,0.1

Type RM Length L Ch R = 1 ,22255.3 ,415.7,427,437.5
XS GIS Cut Line= 2
     1660828.422      315537.579     1661729.029      315902.162
#Sta/Elev= 30
       0  859.92    19.6  859.69    78.5  857.81     265  847.84   431.8  840.81
   549.6     835   568.7   834.7   583.7  834.82   588.8  834.94   618.3  837.79
   637.9  838.95   667.4  839.79   716.4  840.35   736.1  841.26   745.9  843.19
   765.5  850.63   775.3  853.67     795  856.24   804.8  859.45   814.6  865.82
   824.4  874.25   834.2  882.02     844  888.59   853.8  894.78   873.5  905.43
   883.3  910.14   902.9  918.55   912.7  922.14   942.2  931.65   971.6  942.96
#Mann= 3 , 0 , 0
       0     .06       0   568.7    .045       0   583.7     .06       0
Bank Sta=568.7,583.7
XS Rating Curve= 0 ,0
Exp/Cntr=0.3,0.1

Type RM Length L Ch R = 1 ,21828.3 ,163.4,165.2,167.1
XS GIS Cut Line= 2
     1660730.766      315589.662     1661444.741      316294.957
#Sta/Elev= 30
       0  859.89    78.7  857.33    88.6  856.78   118.1  853.68   127.9  852.98
   196.8  850.05   255.8  848.17   275.5  848.05   344.4  846.96   511.6   841.6
   619.9     840   659.2  838.46   718.3  834.74   721.9  834.74   728.1  834.74
   736.9  835.59   737.9  835.69   747.8  839.16   757.6  843.58   767.4  846.17
   777.3  847.21   787.1  850.03     797  856.15   816.6  870.73   836.3  885.81
   846.2  892.49     856  897.83     915  925.16   964.2  947.25  1003.6  964.58
#Mann= 3 , 0 , 0
       0     .06       0   721.9    .045       0   736.9      .1       0
Bank Sta=721.9,736.9
XS Rating Curve= 0 ,0
Exp/Cntr=0.3,0.1

Type RM Length L Ch R = 1 ,21663   ,63.6,63.6,63.6
XS GIS Cut Line= 2
     1660225.273      315162.941      1661436.21      316571.361
#Sta/Elev= 30
       0   956.1    78.6  927.28   117.9  914.44   216.2  887.29   255.5  880.26
   412.8  871.63   540.5  866.88     629  861.55   707.6  861.18   746.9  857.87
     855  855.53   982.8  848.17  1051.6  845.53  1228.4  843.59  1346.4  839.25
  1380.3  834.78  1385.7  834.53  1395.3  836.15  1415.2  845.27  1434.8  848.61
  1444.7  852.35  1454.5  859.88    1484  886.23  1493.8  893.25  1542.9  914.54
  1641.2  961.35  1700.2   986.5  1739.5   997.4  1778.8  1010.5  1857.4 1040.67
#Mann= 3 , 0 , 0
       0     .06       0  1380.3    .045       0  1395.3      .1       0
Bank Sta=1380.3,1395.3
XS Rating Curve= 0 ,0
Exp/Cntr=0.3,0.1

Type RM Length L Ch R = 1 ,21599.5 ,225.6,221.8,217.8
XS GIS Cut Line= 3
     1659990.898       316089.59     1660790.418      315917.367
     1661386.297      316610.424
#Sta/Elev= 30
       0  1117.4    77.9 1084.49   126.6 1065.92   214.2 1026.96   360.2  973.77
   486.8     914   593.9  865.16   613.4  857.44   623.1  854.91   642.6  852.37
   681.6  851.24   749.7   850.6   798.4  851.86   906.3  845.18  1132.4  841.81
  1201.2  838.77  1252.2  834.24  1260.1  834.05  1267.2  835.57  1289.6   845.9
  1309.3  849.84  1319.1  853.37  1368.2  891.01    1378  894.73  1397.7  897.91
  1417.4  904.77  1515.6  953.74  1535.3  962.16  1623.8  996.06  1731.9 1025.28
#Mann= 3 , 0 , 0
       0     .06       0  1252.2    .045       0  1267.2      .1       0
Bank Sta=1252.2,1267.2
XS Rating Curve= 0 ,0
Exp/Cntr=0.3,0.1

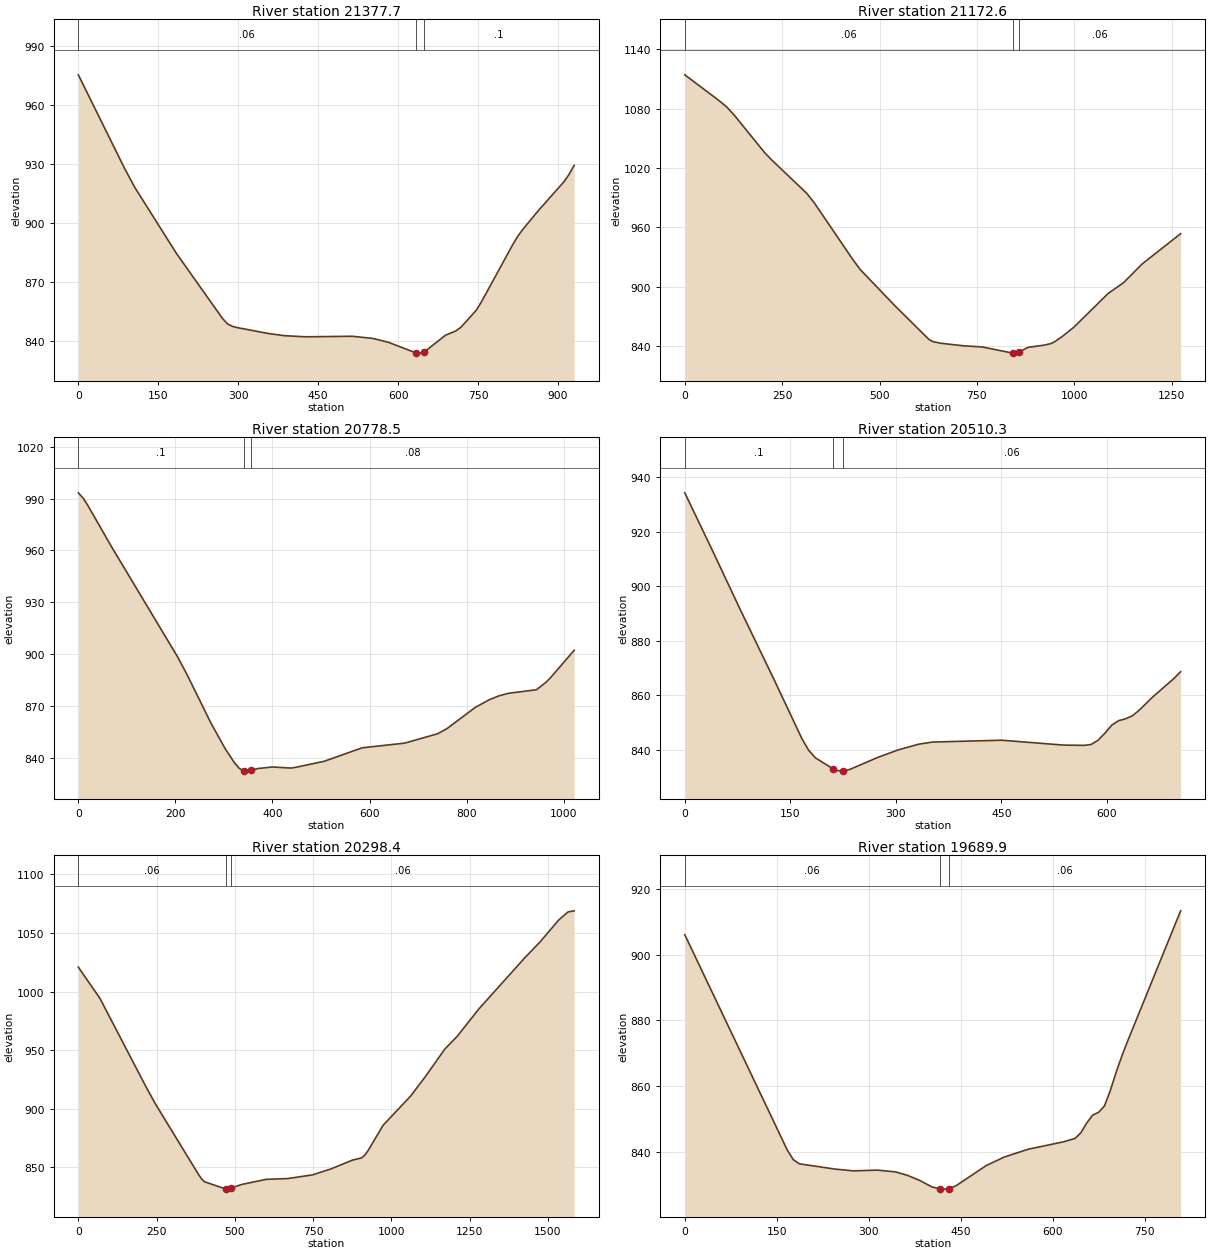
Type RM Length L Ch R = 1 ,21377.7 ,213.4,205.2,196.9
XS GIS Cut Line= 4
     1660342.311      316162.579     1660622.259      316153.898
     1660930.418      316407.804     1661162.623      316503.291
#Sta/Elev= 30
       0  975.51    86.9  927.77   106.2  918.06   183.5  884.79   270.4  851.45
   280.1  848.61   289.8  847.31   299.6  846.68     358  843.68   387.2  842.63
   426.2  842.06   513.8  842.34   552.8  841.24     582  839.25     633  833.93
   640.4  833.75     648  834.38   650.2  834.56     689  842.88   708.3  845.04
     718  846.94     747  855.69   756.6  859.96   814.6  888.73   824.2   893.1
   833.9  896.72   862.8  906.22   911.1     921   920.8   924.8   930.4  929.42
#Mann= 3 , 0 , 0
       0     .06       0     633    .045       0     648      .1       0
Bank Sta=633,648
XS Rating Curve= 0 ,0
Exp/Cntr=0.3,0.1

Type RM Length L Ch R = 1 ,21172.6 ,392.3,394.1,395.2
XS GIS Cut Line= 2
     1659975.839      316268.227     1661178.096      316687.498
#Sta/Elev= 30
       0 1114.05    88.2 1087.93   107.7 1081.59   127.3 1073.18   205.7 1035.13
   225.3 1027.25   313.4  994.26     333  984.44     431  927.74   450.5  917.35
   538.7   881.1   626.8  846.78   636.6  844.63   656.2  842.93     715  840.31
     764  839.11   842.3  832.89   843.8  832.93   852.1  833.15   858.8  834.11
   881.5  838.74   920.7   840.8   940.3  842.51     950  844.39   969.6  849.77
     999  859.03  1087.2  893.15  1126.4  903.94  1175.3  923.25  1273.3  953.54
#Mann= 3 , 0 , 0
       0     .06       0   843.8    .045       0   858.8     .06       0
Bank Sta=843.8,858.8
XS Rating Curve= 0 ,0
Exp/Cntr=0.3,0.1

Type RM Length L Ch R = 1 ,20778.5 ,262,268.2,274.4
XS GIS Cut Line= 3
     1660149.474      316621.912      1660720.22      316873.648
     1661091.314      317016.877
#Sta/Elev= 30
       0  993.29     9.8  990.26    19.5  986.04    68.2   962.2   204.7  898.31
   224.2  888.02   272.9  860.25   302.2  845.42   321.6  837.14   331.4  833.93
   340.8  832.32   341.1  832.27   355.8  832.77   370.4  833.78   399.6  834.67
   438.6  834.04   448.4   834.5   506.8  837.98   584.8  845.76   672.3  848.46
   740.2  853.89   759.6  856.87   817.8  869.14   846.9  873.59   866.3  875.81
   885.8  877.28     944  879.37   963.4  883.65   973.1   886.4  1021.6  902.18
#Mann= 3 , 0 , 0
       0      .1       0   340.8    .045       0   355.8     .08       0
Bank Sta=340.8,355.8
XS Rating Curve= 0 ,0
Exp/Cntr=0.3,0.1

Type RM Length L Ch R = 1 ,20510.3 ,208.2,212,215.5
XS GIS Cut Line= 2
     1660158.719      316851.035      1660702.99      317298.952
#Sta/Elev= 30
       0  934.23    39.2  913.12    78.3   891.7   127.3  865.51   166.4  844.11
   176.2  839.75     186  836.97   210.3  833.07   215.4  832.43   225.2  832.15
   225.3  832.16     235  832.81   274.1  837.16   303.5  839.95   332.9  842.06
   352.4  842.81   450.3  843.49   538.4   841.7   567.8   841.6   577.6  841.92
   587.4  843.46   597.2  846.06     607  849.02   616.8  850.66   626.6  851.34
   636.4  852.44   646.1  854.53   665.7  859.46   695.1  866.05   704.9  868.64
#Mann= 3 , 0 , 0
       0      .1       0   210.3    .045       0   225.3     .06       0
Bank Sta=210.3,225.3
XS Rating Curve= 0 ,0
Exp/Cntr=0.3,0.1

Type RM Length L Ch R = 1 ,20298.4 ,599.1,608.4,618
XS GIS Cut Line= 2
     1659902.054      316830.727     1661004.485       317967.88
#Sta/Elev= 30
       0 1020.82    68.9  994.23   216.4  918.61   245.9   904.3   383.7  844.08
   393.5  840.31   403.3  837.76   471.5  831.52   472.2  831.49   486.5  832.28
   521.4  835.43   600.1  839.84   668.9  840.49   747.6  843.62   806.7  848.69
   875.5  856.22     905  858.16   914.9   860.4   924.7  864.03   973.9  886.05
  1062.4  911.15  1111.6  928.58  1170.6  950.93    1210  961.73  1278.9  984.99
  1426.4 1028.86  1475.6 1042.52  1534.6 1061.03  1564.1 1067.86  1583.8 1068.82
#Mann= 3 , 0 , 0
       0     .06       0   471.5    .045       0   486.5     .06       0
Bank Sta=471.5,486.5
XS Rating Curve= 0 ,0
Exp/Cntr=0.3,0.1

Type RM Length L Ch R = 1 ,19689.9 ,304.6,305.8,310.8
XS GIS Cut Line= 3
     1659745.523      317173.864     1659910.453      317699.037
     1660081.894      317892.179
#Sta/Elev= 30
       0  906.11   167.1  840.53   176.9  837.61   186.8  836.32   245.7   834.7
   275.2  834.17   314.6   834.4     344  833.85   363.7  832.77   383.4  831.24
     403  829.29   415.6  828.71   422.7  828.61   430.6  828.73   442.3  829.63
   491.5  835.77     521  838.38     560  840.76   617.4  843.01   636.6  844.06
   646.1  845.81   655.7  848.78   665.2  851.15   674.8  851.99   684.4  853.92
   693.9  858.57   703.5   864.2   713.1  869.27   722.6  873.84   808.7  913.39
#Mann= 3 , 0 , 0
       0     .06       0   415.6    .045       0   430.6     .06       0
Bank Sta=415.6,430.6
XS Rating Curve= 0 ,0
Exp/Cntr=0.3,0.1

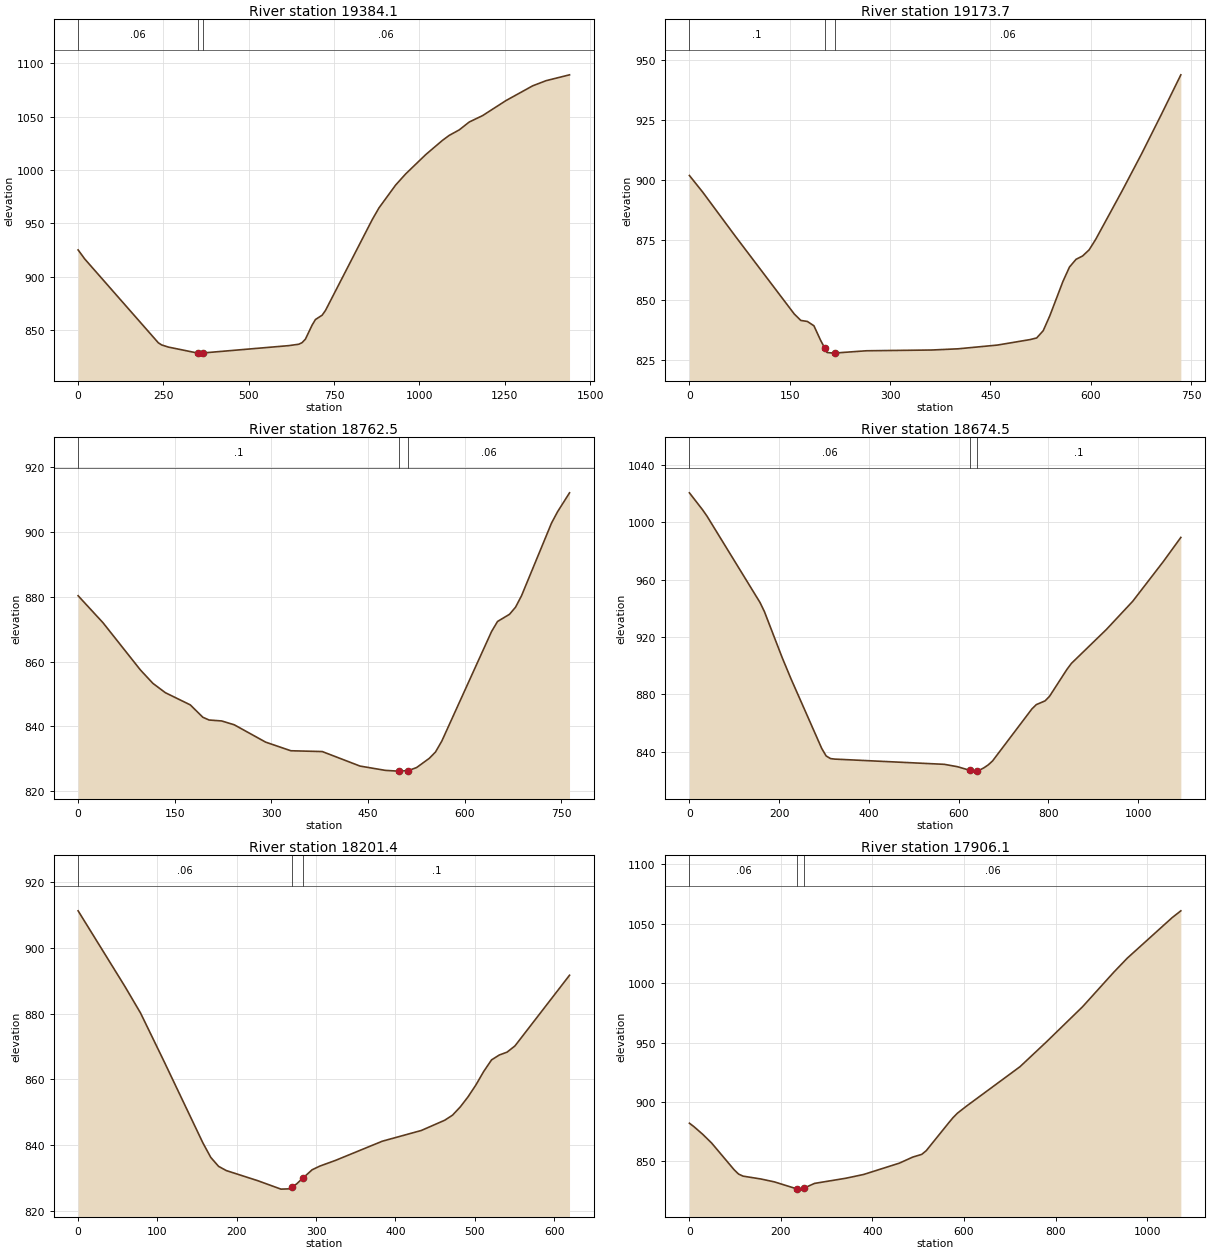
Type RM Length L Ch R = 1 ,19384.1 ,201.7,210.4,214.8
XS GIS Cut Line= 3
     1659578.703      317150.605     1659613.426      317805.987
     1659552.662      318587.237
#Sta/Elev= 30
       0  924.93    19.6  916.37   235.1  837.82   244.9  835.84   264.5  833.84
   350.6  828.21   352.6  828.17   365.6  828.32   617.1  835.19   646.5  836.51
   656.3  837.99   666.1  841.33   685.7  854.48   695.5  859.69   715.1  863.74
   724.9  868.22     862  953.43   881.6  964.35   930.6  985.83     960  996.24
  1018.7 1014.32  1067.7 1027.65  1087.3 1032.28  1116.7 1037.44  1146.1 1044.85
  1185.2 1050.84  1253.8 1064.96  1332.2  1078.8  1371.3  1083.6  1439.9 1089.07
#Mann= 3 , 0 , 0
       0     .06       0   350.6    .045       0   365.6     .06       0
Bank Sta=350.6,365.6
XS Rating Curve= 0 ,0
Exp/Cntr=0.3,0.1

Type RM Length L Ch R = 1 ,19173.7 ,415.7,411.2,406.3
XS GIS Cut Line= 2
     1659435.193      317217.266     1659365.748      317948.603
#Sta/Elev= 30
       0  901.98    19.6  895.15    68.6  876.68   156.7  844.23   166.5  841.54
   176.3  841.11   186.1  839.31   195.9  833.37   202.5  829.86   205.7  828.16
   215.5   827.9   217.5  827.94   264.5  828.88   362.4   829.2   401.6   829.7
   460.4  831.26   509.3  833.55   519.1  834.23   528.9  837.27   538.7  843.46
   558.3  857.77   568.1   863.8   577.9  867.02   587.7  868.41   597.5  870.98
   607.3  875.34   646.5  895.42   675.9  911.01   705.2   927.3   734.6  943.98
#Mann= 3 , 0 , 0
       0      .1       0   202.5    .045       0   217.5     .06       0
Bank Sta=202.5,217.5
XS Rating Curve= 0 ,0
Exp/Cntr=0.3,0.1

Type RM Length L Ch R = 1 ,18762.5 ,100.5,88,75.8
XS GIS Cut Line= 4
     1659062.234      317153.596     1659075.636      317346.699
     1659119.703      317774.148     1659198.953      317889.273
#Sta/Elev= 30
       0  880.36    38.7  872.01    96.8  857.43   116.1  853.31   135.5  850.42
   174.2  846.66   193.6  842.85   203.3  841.99   222.9   841.7   242.4  840.52
   291.2  835.16   330.3   832.5   379.1  832.25   437.7  827.77   476.8  826.45
   496.3  826.21   497.9  826.21   512.9  826.38   525.6  827.32   545.2  830.15
   554.9  832.11   564.7  835.49   641.9  869.29   651.2  872.41   669.9  874.64
   679.2  876.83   688.5  880.37   735.1  902.82   744.4  906.28     763  912.13
#Mann= 3 , 0 , 0
       0      .1       0   497.9    .045       0   512.9     .06       0
Bank Sta=497.9,512.9
XS Rating Curve= 0 ,0
Exp/Cntr=0.3,0.1

Type RM Length L Ch R = 1 ,18674.5 ,483.5,473,464
XS GIS Cut Line= 3
     1658592.779      317250.897     1658834.966      317435.792
     1659308.925      318068.605
#Sta/Elev= 30
       0 1020.56    29.5 1008.64    39.3 1004.23   157.3  944.05   167.1   937.7
   206.4  905.83   226.1  890.97   294.9  842.17   304.7  836.94   314.5  835.09
   324.2  834.73   568.2  831.08   597.5  829.42   624.9  826.91   636.6  826.34
   639.9  826.56   646.3  826.99   656.1  828.61   665.8  830.64   675.6  833.43
   763.5  869.81   773.2  872.76   792.7  875.37   802.5   878.5   841.5  897.38
   851.3  901.49   929.4  925.21     988  944.86  1056.3  972.62  1095.3  989.44
#Mann= 3 , 0 , 0
       0     .06       0   624.9    .045       0   639.9      .1       0
Bank Sta=624.9,639.9
XS Rating Curve= 0 ,0
Exp/Cntr=0.3,0.1

Type RM Length L Ch R = 1 ,18201.4 ,289.7,295.4,298.9
XS GIS Cut Line= 2
      1658454.29      317863.968     1658977.293      318195.999
#Sta/Elev= 30
       0  911.26      59  888.24    78.7  880.15   108.2  865.48   157.3  840.61
   167.2   836.2     177  833.48   186.8  832.18   226.2  829.12   255.7  826.53
   265.5  826.61   269.1  827.15   275.3  828.08   284.1  830.05     295  832.42
   304.8  833.55   324.5  835.28   383.5  841.12   432.7  844.39   462.2  847.51
     472  849.05   481.8  851.57   491.7  854.68   501.5  858.26   511.3  862.35
   521.2  865.88     531  867.37   540.8  868.24   550.7  870.13   619.5  891.65
#Mann= 3 , 0 , 0
       0     .06       0   269.1    .045       0   284.1      .1       0
Bank Sta=269.1,284.1
XS Rating Curve= 0 ,0
Exp/Cntr=0.3,0.1

Type RM Length L Ch R = 1 ,17906.1 ,336.4,347.7,358.9
XS GIS Cut Line= 2
     1658333.044      318070.744     1659144.676      318773.869
#Sta/Elev= 30
       0  882.16     9.8  879.31    29.3  872.75    48.8  865.37    97.6  843.04
   107.4  839.36   117.2  837.63   156.2  835.22   185.5  832.81   235.9  826.76
     244  826.69   250.9  827.63   273.3   831.5   341.7  835.85   380.7  839.03
   458.8  848.57   488.1  853.68   507.6  855.93   517.4  859.02   566.2  882.32
     576  886.85   585.7  890.64   605.2   896.5   722.4  929.76     781  950.96
   859.1  980.23   927.4 1009.33   956.7 1021.09  1054.3 1055.05  1073.8 1060.95
#Mann= 3 , 0 , 0
       0     .06       0   235.9    .045       0   250.9     .06       0
Bank Sta=235.9,250.9
XS Rating Curve= 0 ,0
Exp/Cntr=0.3,0.1

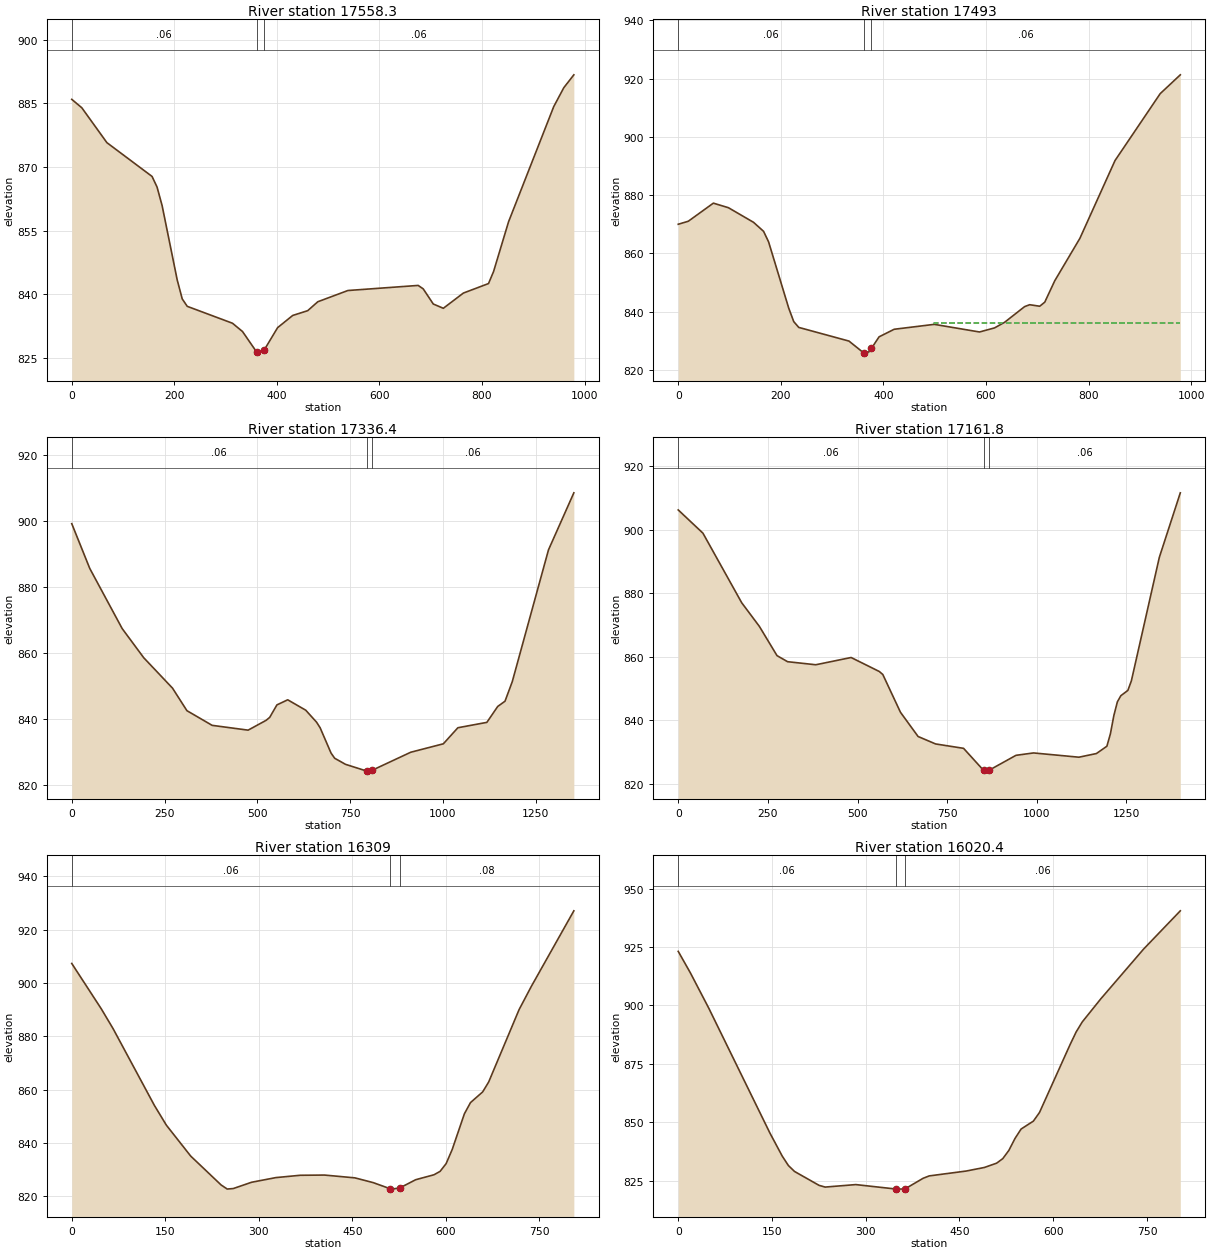
Type RM Length L Ch R = 1 ,17558.3 ,65.4,65.4,65.4
XS GIS Cut Line= 2
     1658126.315      318108.253     1658470.065       319024.92
#Sta/Elev= 30
       0  885.95    19.6  883.96    68.5  875.74   156.6  867.77   166.4  865.24
   176.2  860.88   205.6  843.38   215.4   838.9   225.2  837.15   313.3  833.17
   332.9  831.22   360.4   826.4   362.2  826.12   375.4  826.89   401.4  832.13
   430.8     835   460.1  836.13   479.7  838.23   538.4  840.88   675.5  842.08
   685.3  841.27   704.9   837.7   724.5  836.69   763.6  840.28   812.6  842.52
   822.4  845.33   851.7  857.08   939.8  884.24   959.4  888.69     979  891.73
#Mann= 3 , 0 , 0
       0     .06       0   360.4    .045       0   375.4     .06       0
Bank Sta=360.4,375.4
XS Rating Curve= 0 ,0
Exp/Cntr=0.3,0.1

Type RM Length L Ch R = 1 ,17493   ,161.6,156.6,151.5
XS GIS Cut Line= 2
     1658067.287      318136.031     1658411.037      319052.698
#Sta/Elev= 30
       0  869.97    19.6     871    68.5  877.22    97.9  875.65   146.8  870.64
   166.4  867.54   176.2  863.92   215.4   841.2   225.2  836.55     235  834.55
   332.9  829.86   361.7  825.79   362.2  825.72     372  826.17   376.7  827.34
   391.6  831.31     421  833.91   499.3   835.6   587.4  832.98   616.8  834.38
   636.4  836.31   675.5   841.7   685.3  842.34   704.9  841.82   714.7  843.22
   734.2  850.57   783.2  865.14   851.7  891.85   939.8  914.82     979  921.28
#Mann= 3 , 0 , 0
       0     .06       0   361.7    .045       0   376.7     .06       0
#XS Ineff= 2 , 0
                          498.59          836.03
Permanent Ineff=
       F       F
Bank Sta=361.7,376.7
XS Rating Curve= 0 ,0
Exp/Cntr=0.3,0.1

Type RM Length L Ch R = 1 ,17336.4 ,176.1,174.6,173
XS GIS Cut Line= 3
      1657903.38      317748.214     1657966.314      318394.915
     1658343.328      318988.462
#Sta/Elev= 30
       0  899.26    48.5  885.68   135.8  867.44     194  858.58   271.5  849.36
   310.3  842.53   378.2  838.08   475.2  836.62   523.7   839.6   533.4   840.5
   552.8  844.28   581.9  845.83   630.4  842.68   659.5  839.06   669.3  837.33
   698.6  829.68   708.4   828.1   737.6  826.25   794.6  824.22   796.2  824.19
   809.6  824.46   913.4  829.92  1001.3  832.48  1040.4  837.35  1118.5  838.98
  1147.8  843.81  1167.4   845.4  1186.9   851.3  1284.6  891.32  1352.9  908.62
#Mann= 3 , 0 , 0
       0     .06       0   794.6    .045       0   809.6     .06       0
Bank Sta=794.6,809.6
XS Rating Curve= 0 ,0
Exp/Cntr=0.3,0.1

Type RM Length L Ch R = 1 ,17161.8 ,848.6,852.8,856.9
XS GIS Cut Line= 3
     1657334.804      317928.335     1657775.342      318431.808
     1658218.328      319013.635
#Sta/Elev= 30
       0  906.21    68.9   898.9   177.1     877   226.3  869.58   275.5  860.38
     305  858.47   383.7  857.51   482.1  859.79   560.8  855.39   570.6  854.44
   619.8  842.57     669  834.94   717.8   832.6   795.8  831.22   851.8  824.26
   854.2  824.05   866.8  824.32     942  829.02   990.8  829.77  1117.5  828.43
  1166.3  829.58  1195.5  831.88  1205.3  835.77    1215  841.56  1224.8  845.85
  1234.5  847.78    1254  849.44  1263.8  852.44  1341.8   891.3  1400.3  911.59
#Mann= 3 , 0 , 0
       0     .06       0   851.8    .045       0   866.8     .06       0
Bank Sta=851.8,866.8
XS Rating Curve= 0 ,0
Exp/Cntr=0.3,0.1

Type RM Length L Ch R = 1 ,16309   ,299.1,288.6,278.6
XS GIS Cut Line= 3
     1657051.948      318481.243     1657150.342      318583.717
     1657456.026      319172.561
#Sta/Elev= 30
       0  907.31    47.4  890.29    66.3  882.88   132.6   854.1   151.8   846.7
   190.8  835.13   239.6   824.3   249.4  822.77   259.2  822.96   288.4  825.31
   327.4  827.06   366.5  827.93   405.5  828.01   454.3  826.96   483.6  825.18
     511  822.87   512.8  822.74     526  823.16   551.8  826.27   581.1  828.12
   590.9  829.39   600.6   832.3   610.4  837.62   629.9  850.97   639.7  855.17
   659.2  859.17   668.9  862.91   717.7  890.04   737.2  898.68   805.5  927.04
#Mann= 3 , 0 , 0
       0     .06       0     511    .045       0     526     .08       0
Bank Sta=511,526
XS Rating Curve= 0 ,0
Exp/Cntr=0.3,0.1

Type RM Length L Ch R = 1 ,16020.4 ,384.8,389.2,392.8
XS GIS Cut Line= 2
     1656823.392      318684.693     1657326.099      319311.196
#Sta/Elev= 30
       0  923.12    19.6  913.84      49  898.73   146.9  845.24   166.5  835.43
   176.3  831.43   186.1   828.9   225.3  822.96   235.1  822.22   284.1  823.28
   347.7   821.4   352.6  821.34   362.7  821.41   391.8  825.98   401.6     827
   460.4  829.07   489.8  830.61   509.4  832.45   519.2  834.38     529  837.92
   538.8  843.03   548.6  847.07   568.2  850.45     578  854.15   626.9  883.18
   636.7  888.65   646.5  892.94   675.9  902.74   744.5  924.09   803.3  940.48
#Mann= 3 , 0 , 0
       0     .06       0   347.7    .045       0   362.7     .06       0
Bank Sta=347.7,362.7
XS Rating Curve= 0 ,0
Exp/Cntr=0.3,0.1

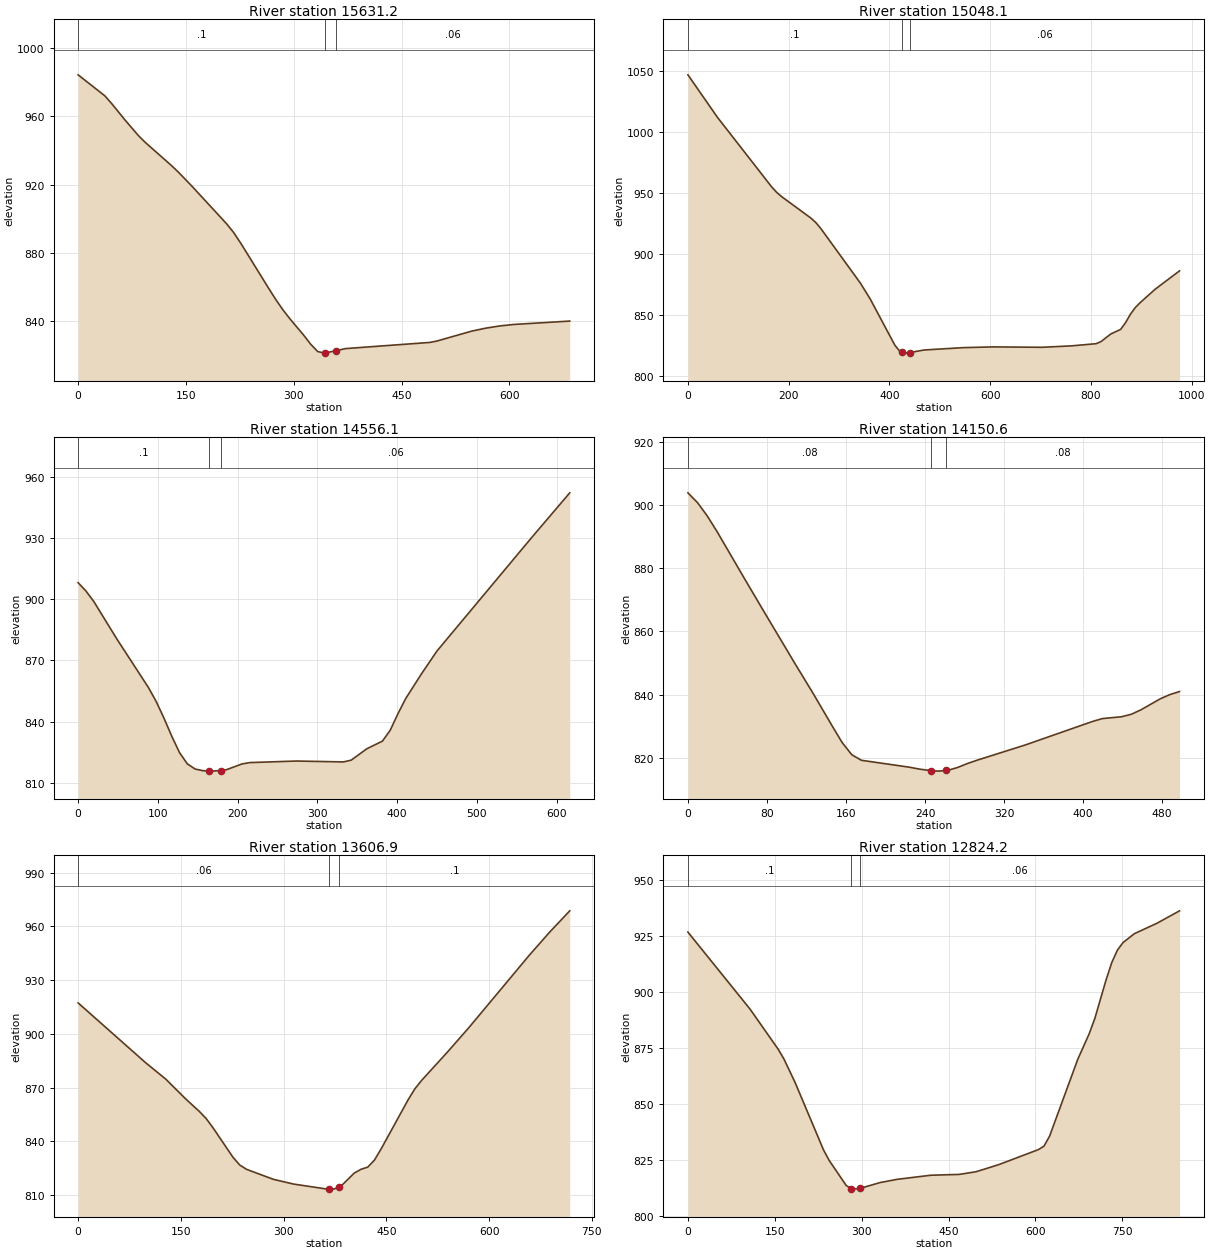
Type RM Length L Ch R = 1 ,15631.2 ,600.4,583.1,566.2
XS GIS Cut Line= 3
     1656468.918      318798.561     1656578.381      318925.564
     1656930.852       319302.77
#Sta/Elev= 30
       0   984.4    37.3  972.04    46.6   967.6    65.2  957.95    83.8  948.82
    93.2  944.88   130.4  931.03   139.7  927.29   158.4  919.11   206.6  897.09
   216.4  891.96   226.1  885.83   265.1  859.28   274.8  852.84   284.6  846.86
   294.3   841.6   313.8  831.84   323.5  826.57   333.3  822.24     343  821.32
   343.3  821.34   358.3  822.75   372.2  823.98   489.1  827.58   498.8  828.37
   547.6  834.22     567  835.94   586.5  837.24     606  838.12   683.9   840.1
#Mann= 3 , 0 , 0
       0      .1       0   343.3    .045       0   358.3     .06       0
Bank Sta=343.3,358.3
XS Rating Curve= 0 ,0
Exp/Cntr=0.3,0.1

Type RM Length L Ch R = 1 ,15048.1 ,489.4,492,493.9
XS GIS Cut Line= 3
     1655924.214      319460.453     1656274.601      319497.499
     1656896.436      319545.089
#Sta/Elev= 30
       0 1046.59    58.7 1011.75   166.4  954.74   176.2  950.31     186  946.84
   244.7  929.08   254.5  925.32   264.3  920.45   342.6  875.86   362.1  862.83
   410.8  825.17   420.6  820.14   425.7  819.34   430.3  818.62   440.7  819.09
   469.3  821.21   547.2  823.12   605.7  823.72   703.2   823.4   761.6  824.57
   810.3  826.35   820.1  828.06   839.6  834.32   859.1  838.07   868.8  843.59
   878.6  850.55   888.3  856.01     898  860.02   927.3  870.87     976  886.02
#Mann= 3 , 0 , 0
       0      .1       0   425.7    .045       0   440.7     .06       0
Bank Sta=425.7,440.7
XS Rating Curve= 0 ,0
Exp/Cntr=0.3,0.1

Type RM Length L Ch R = 1 ,14556.1 ,395.1,405.4,413.8
XS GIS Cut Line= 2
     1656236.689      319955.293     1656844.328       320059.46
#Sta/Elev= 30
       0  908.04     9.8  903.99    19.6  898.88    48.9  880.31    88.1   856.8
    97.9  849.93   107.6  841.81   117.4  832.95   127.2  824.88     137  819.38
   146.8  816.85   156.6  816.05   164.6  815.88   166.4  815.84   179.6  816.11
   185.9  816.52   205.5  819.35   215.3  820.02     274  820.78   332.7  820.34
   342.5  821.22   362.1   826.8   381.6  830.52   391.4  835.86   401.2  844.03
     411   851.5   430.6  863.46   450.1  874.67   567.6   929.6   616.5  952.02
#Mann= 3 , 0 , 0
       0      .1       0   164.6    .045       0   179.6     .06       0
Bank Sta=164.6,179.6
XS Rating Curve= 0 ,0
Exp/Cntr=0.3,0.1

Type RM Length L Ch R = 1 ,14150.6 ,532.8,543.7,554.6
XS GIS Cut Line= 2
     1656108.675      320222.172     1656529.377      320487.666
#Sta/Elev= 30
       0  903.87     9.8  900.74    19.5  896.59    29.3  891.71    58.5  876.05
      78  865.73   107.3  850.36   126.8  840.33   146.3  829.92   156.1  824.81
   165.8  820.98   175.6   819.2   224.4     817   234.1  816.42   245.8  815.92
   253.6  815.77   260.8  815.98   263.4  816.05   273.1  816.94   282.9  818.18
   292.6  819.22   341.4  824.05   409.7  831.52   419.4   832.4   438.9  832.99
   448.7  833.77   458.4  835.17     478  838.66   487.7     840   497.5  840.96
#Mann= 3 , 0 , 0
       0     .08       0   245.8    .045       0   260.8     .08       0
Bank Sta=245.8,260.8
XS Rating Curve= 0 ,0
Exp/Cntr=0.3,0.1

Type RM Length L Ch R = 1 ,13606.9 ,771.2,782.7,793.6
XS GIS Cut Line= 2
     1655750.578      320411.022     1656110.821      321031.682
#Sta/Elev= 30
       0  917.32    98.3  883.99   127.8  874.79   157.3  863.59     177  856.68
   186.8  852.78   196.6  847.72   226.1  831.07   235.9  826.78   245.8  824.36
   285.1  818.76   314.6  816.12   363.7   813.3     366  813.32   373.6  813.39
     381  814.48   383.4  814.84     403  822.26   412.9  824.37   422.7  825.58
   432.5   829.5   442.4  835.84   481.7  863.21   491.5   869.3   501.4  874.03
   540.7  890.55   570.2  903.43   658.6  943.97   688.1  956.78   717.6  968.75
#Mann= 3 , 0 , 0
       0     .06       0     366    .045       0     381      .1       0
Bank Sta=366,381
XS Rating Curve= 0 ,0
Exp/Cntr=0.3,0.1

Type RM Length L Ch R = 1 ,12824.2 ,469.2,469.2,469.1
XS GIS Cut Line= 2
     1655195.023      320402.342     1655221.089      321250.818
#Sta/Elev= 30
       0  926.63   107.3  892.33   156.1  874.39   165.9  870.08   185.4  859.47
   234.2  829.61   243.9  824.97   273.2  813.84   282.4  812.27     283  812.17
   297.4  812.51   331.7  815.08     361  816.52   419.6  818.36   468.4  818.72
   497.6  819.92   536.6  823.06     605  829.75   614.7  831.27   624.5  835.74
   673.2  869.99   692.8  881.29   702.5  888.04     722  905.28   731.8     913
   741.6  918.58   751.3  921.95   770.8   925.9   809.8  930.54   848.9  936.09
#Mann= 3 , 0 , 0
       0      .1       0   282.4    .045       0   297.4     .06       0
Bank Sta=282.4,297.4
XS Rating Curve= 0 ,0
Exp/Cntr=0.3,0.1