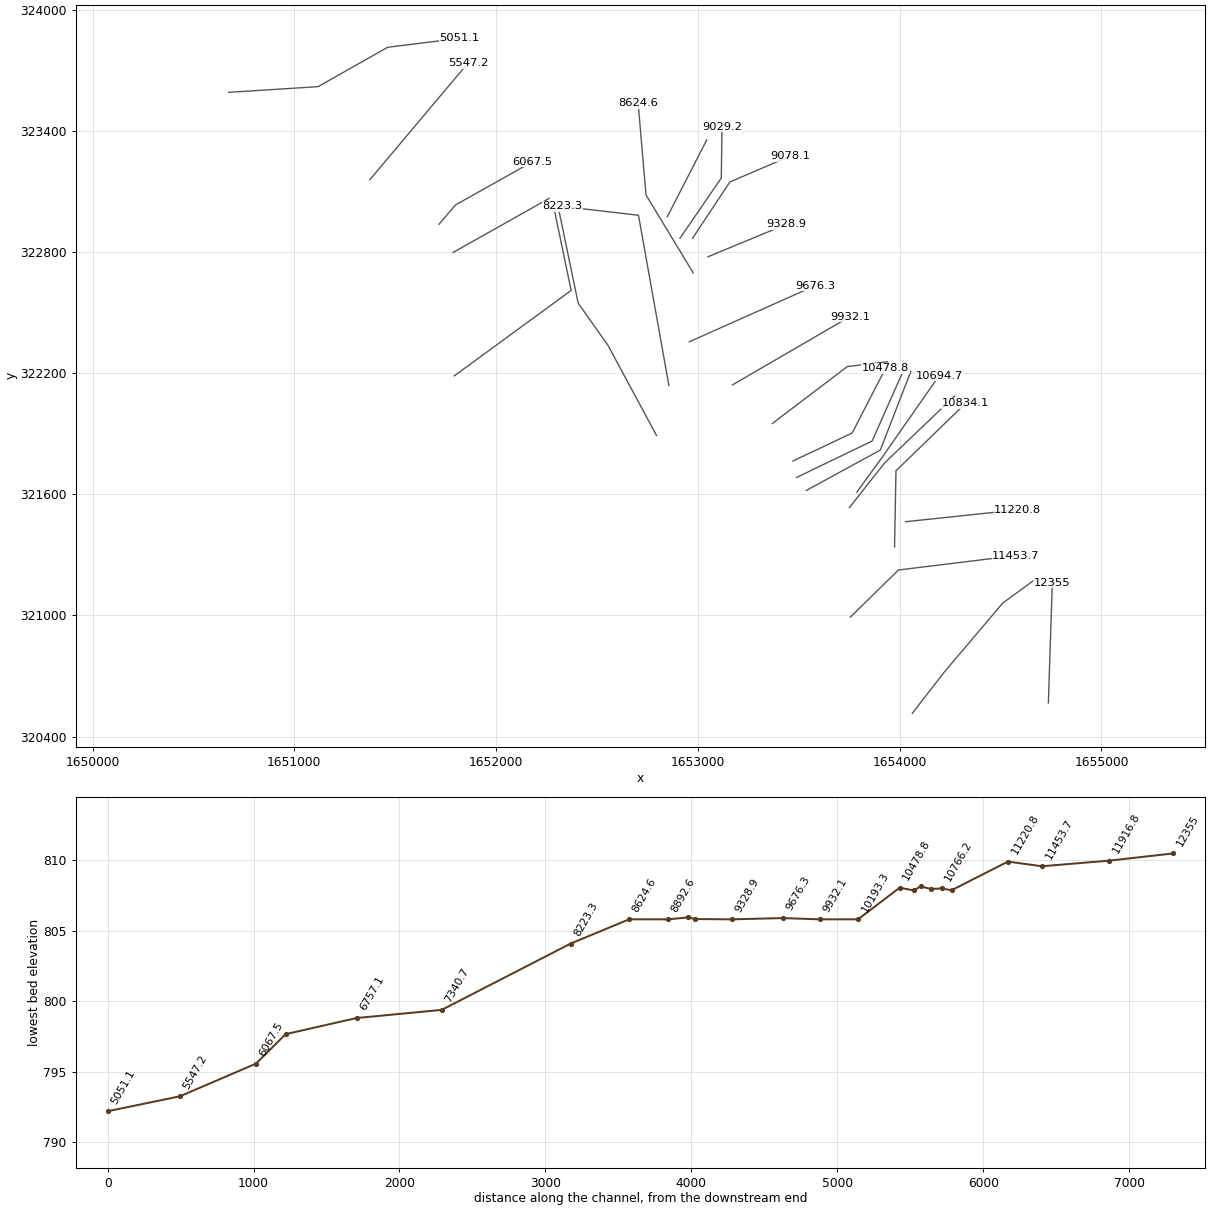
HEC-RAS study RBNSONFRK.prj: RBNSONFRK

--- RBNSONFRK.g01 (geometry) --- (continued)

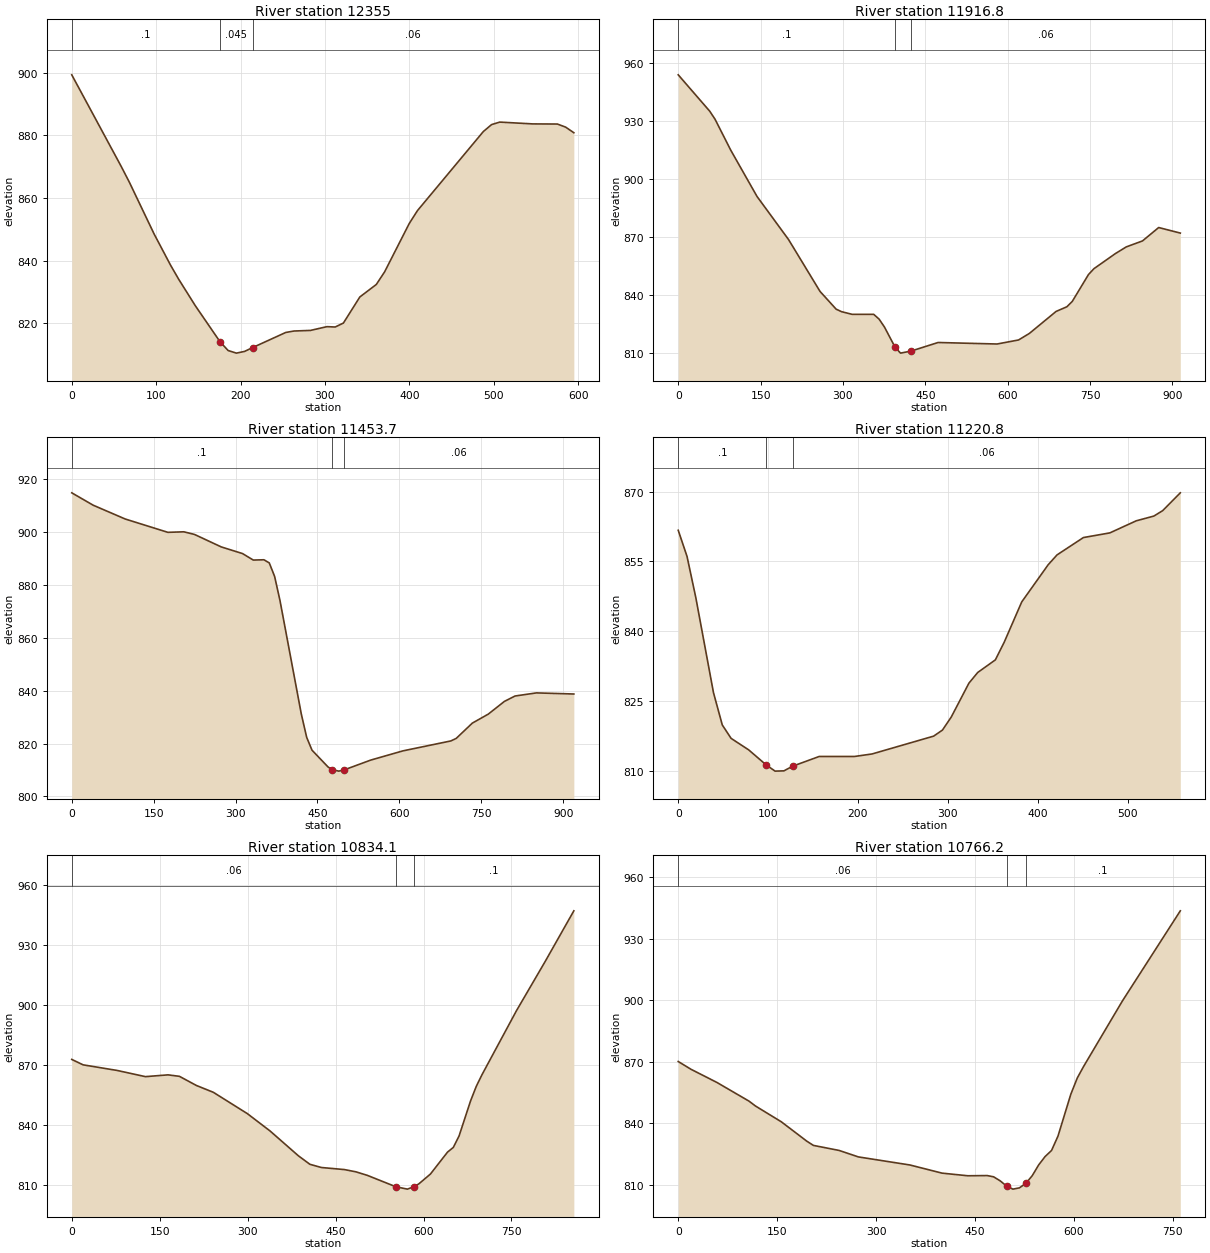
Type RM Length L Ch R = 1 ,12355   ,453.3,438.2,422.8
XS GIS Cut Line= 2
     1654736.844      320567.181     1654756.655       321161.89
#Sta/Elev= 30
       0  899.32    58.5  870.12    68.3  865.01    97.6   848.5   117.1  838.54
   126.8  834.02   146.3  825.65   175.6  814.14   185.3   811.3   195.1  810.47
   204.8  811.02   214.5  812.26   253.6  817.07   263.4  817.53   282.9  817.72
   302.4  818.92   312.2  818.81   321.9  820.07   341.4   828.4   360.9  832.39
   370.7  836.39   399.9  851.83   409.7  855.98   487.7   881.2   497.5  883.43
   507.2  884.23   546.3  883.65   575.5  883.61   585.3  882.62     595  880.83
#Mann= 3 , 0 , 0
       0      .1       0   175.6    .045       0   214.5     .06       0
Bank Sta=175.6,214.5
XS Rating Curve= 0 ,0
Exp/Cntr=0.3,0.1

Type RM Length L Ch R = 1 ,11916.8 ,480.1,463.1,445.8
XS GIS Cut Line= 4
     1654062.234      320515.141     1654220.654      320719.134
     1654511.453      321062.016     1654678.554      321183.544
#Sta/Elev= 30
       0  953.73    57.4  934.93      67  930.82    95.7  914.78   143.5   890.9
   200.9  868.65   258.3  841.83   287.6  832.68   297.4  831.38   316.9  829.99
     356     830   365.8  827.55   375.6  823.46   395.1  812.94   404.9  809.96
   424.4  811.05   473.3  815.45   580.8  814.67   619.9  816.76   639.5  820.12
   688.3  831.51   707.9  833.91   717.7  836.67   747.2  850.53   757.1  853.57
   796.4  861.41   816.1  864.84   845.6  867.92   875.1  874.84   914.5  871.98
#Mann= 3 , 0 , 0
       0      .1       0   395.1    .045       0   424.4     .06       0
Bank Sta=395.1,424.4
XS Rating Curve= 0 ,0
Exp/Cntr=0.3,0.1

Type RM Length L Ch R = 1 ,11453.7 ,233.1,232.9,232.4
XS GIS Cut Line= 3
     1653756.245      320992.571     1653993.787      321225.039
     1654576.557      321296.391
#Sta/Elev= 30
       0  914.86    39.1  910.19    97.8  904.96     176  899.91   205.3  900.11
   224.8  899.11   273.7   894.4   312.8  891.87   332.4  889.42   351.9  889.53
   361.7  888.35   371.5  883.23   381.3  874.14   420.4  831.14   430.2  822.35
     440  817.48   469.4  811.12   476.5  810.17   488.9  809.56   498.7  810.02
   547.6  813.74   606.4  817.22   694.4  820.99   704.2  821.96   733.6  827.73
   762.9  831.14   792.3  835.94   811.8  837.98     851  839.16   919.5  838.74
#Mann= 3 , 0 , 0
       0      .1       0   476.5    .045       0   498.7     .06       0
Bank Sta=476.5,498.7
XS Rating Curve= 0 ,0
Exp/Cntr=0.3,0.1

Type RM Length L Ch R = 1 ,11220.8 ,371.3,386.7,402.2
XS GIS Cut Line= 2
     1654029.377      321464.228     1654584.932      321522.822
#Sta/Elev= 30
       0   861.7     9.8  856.07    19.6  847.18    39.2  826.79      49  819.83
    58.8  816.94    78.4  814.46      98   811.2   107.8  809.89   117.6  809.95
   127.4  810.96   156.8  813.04     196  813.04   215.6  813.58   284.2  817.42
     294  818.73   303.8  821.54   323.4  828.81   333.2  831.11   352.8  833.82
   362.6  837.59   382.2   846.3   411.6  854.29   421.4   856.4   450.8  860.14
   480.2  861.14   509.6  863.74   529.2  864.76     539  865.93   558.6  869.76
#Mann= 3 , 0 , 0
       0      .1       0      98    .045       0   127.4     .06       0
Bank Sta=98,127.4
XS Rating Curve= 0 ,0
Exp/Cntr=0.3,0.1

Type RM Length L Ch R = 1 ,10834.1 ,68.3,68,67.6
XS GIS Cut Line= 3
     1653974.669       321339.36     1653981.614      321716.096
     1654325.967      322049.877
#Sta/Elev= 30
       0   872.7    19.3  869.99    77.3  867.19   125.6  864.09   164.2  864.98
   183.6  864.25   212.6  859.67   241.5  856.26   299.5   845.6   338.2  836.94
   386.6  824.51   406.2  820.27   425.7  818.67   464.9  817.64   484.5  816.52
     504  814.76     553  809.03   572.5  807.86   583.7  809.08   592.1  810.51
   611.7  815.38     641  826.38   650.8   828.7   660.6  834.42   680.2  851.93
     690  859.25   699.8   865.1   758.5  897.04   807.4  921.61   856.4  946.98
#Mann= 3 , 0 , 0
       0     .06       0     553    .045       0   583.7      .1       0
Bank Sta=553,583.7
XS Rating Curve= 0 ,0
Exp/Cntr=0.3,0.1

Type RM Length L Ch R = 1 ,10766.2 ,67,71.5,76
XS GIS Cut Line= 3
     1653750.711      321533.804     1653926.058      321756.026
     1654272.148      322086.335
#Sta/Elev= 30
       0  870.21    19.5  866.39    58.6  860.01   107.4  850.88   117.1  848.52
   156.2  840.85   195.2  831.32     205  829.31     244  826.85   273.3  823.69
   351.4  819.76   400.2  815.78   439.3   814.5   468.6   814.6   478.3     814
   488.1  812.07   497.9  809.52   507.6  807.99   517.4   808.6   527.2  810.78
   536.9  814.53   546.7   819.8   556.4  823.86   566.2  826.83     576  833.86
   595.5  854.32   605.3  862.21     615  867.89   673.6  899.69   761.5  943.67
#Mann= 3 , 0 , 0
       0     .06       0   497.9    .045       0   527.2      .1       0
Bank Sta=497.9,527.2
XS Rating Curve= 0 ,0
Exp/Cntr=0.3,0.1

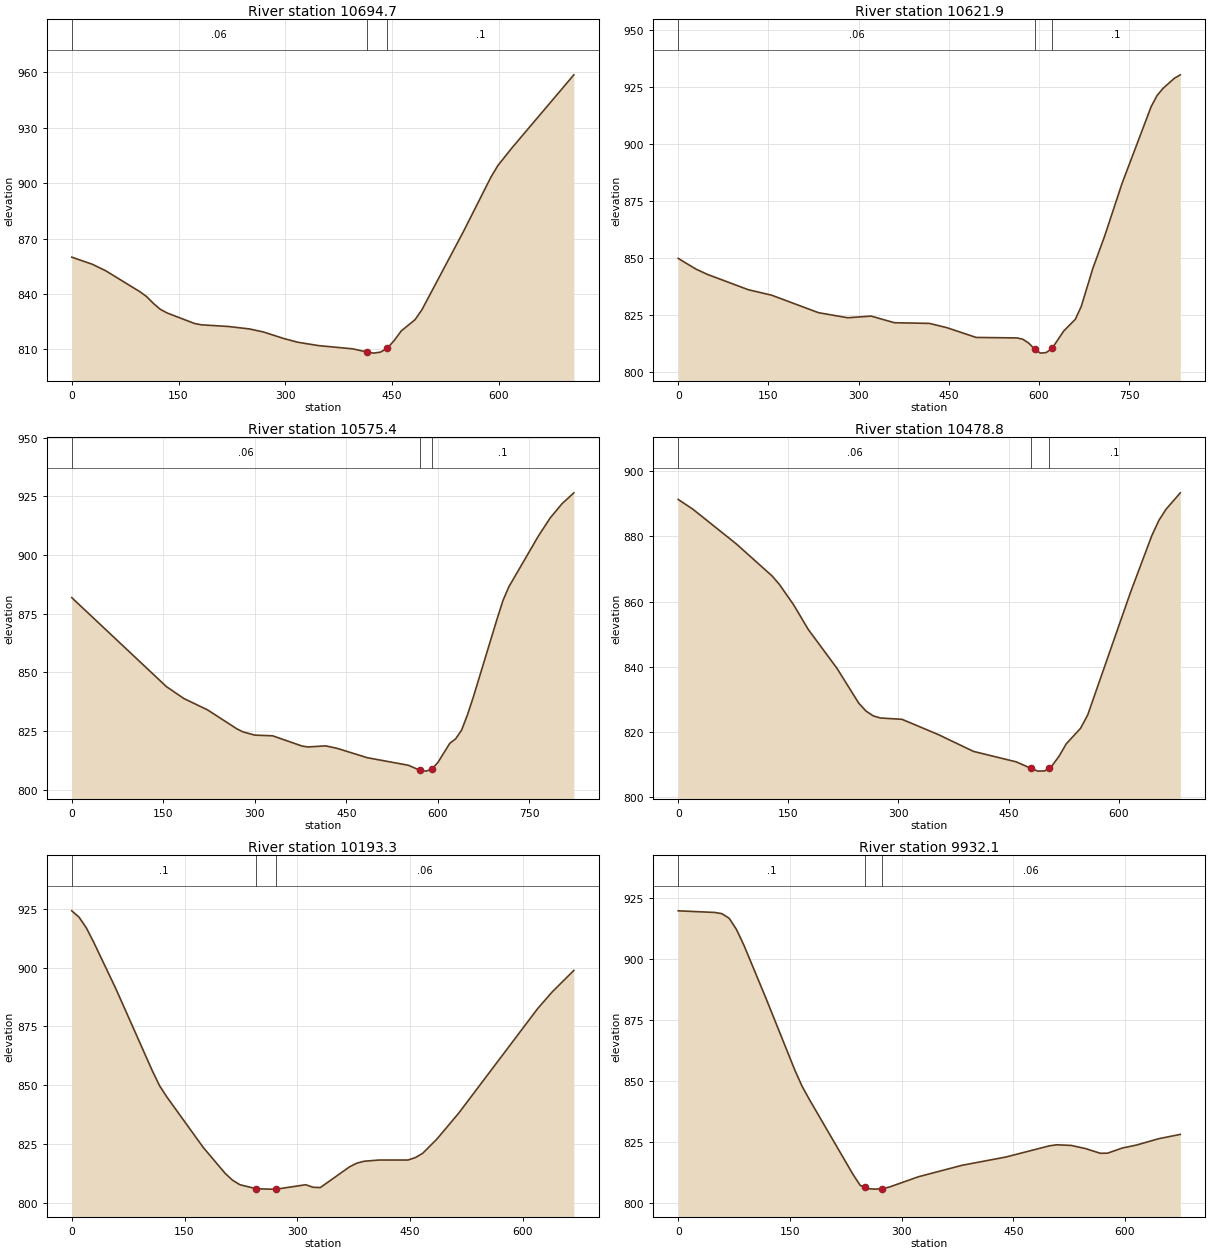
Type RM Length L Ch R = 1 ,10694.7 ,67.3,72.8,78.1
XS GIS Cut Line= 3
     1653787.773      321610.641     1653917.378      321789.012
     1654195.155      322186.582
#Sta/Elev= 30
       0   859.9    28.8  856.08    47.9   852.5    95.9  841.16   105.4  838.48
     115  834.76   124.6  831.62   134.2  829.66   172.6  823.98   182.1  823.28
   220.5  822.36   249.6  821.05     269  819.44   298.1  815.84   317.5  813.85
   346.6  812.03   395.1  810.25   414.5  808.58   424.2  807.95   433.9  808.51
   443.6  810.69   453.3   814.9     463  819.98   482.4  826.07   492.1  831.49
   550.3  873.73   589.1  903.31   598.8  909.53   618.2  918.92   705.5  958.62
#Mann= 3 , 0 , 0
       0     .06       0   414.5    .045       0   443.6      .1       0
Bank Sta=414.5,443.6
XS Rating Curve= 0 ,0
Exp/Cntr=0.3,0.1

Type RM Length L Ch R = 1 ,10621.9 ,47.5,46.4,45.4
XS GIS Cut Line= 3
     1653537.169      321618.874     1653904.092      321818.974
     1654055.134      322207.863
#Sta/Elev= 30
       0  849.78    29.2  845.12    48.6  842.74   116.6  836.01   155.5  833.59
   233.3  825.91   281.9  823.68   320.7  824.42   359.6   821.5   417.9   821.2
     447  819.31   495.6  815.03   563.5  814.81   573.2  814.23   582.9  812.55
   592.6  809.97   602.3  808.13     612  808.38   621.7  810.17   641.1  817.83
   660.5  823.02   670.2  828.55   689.6  845.37     709   859.4   738.1  882.68
   786.6  916.51   796.3  921.34     806  924.45   825.4  929.03   835.1   930.5
#Mann= 3 , 0 , 0
       0     .06       0   592.6    .045       0   621.7      .1       0
Bank Sta=592.6,621.7
XS Rating Curve= 0 ,0
Exp/Cntr=0.3,0.1

Type RM Length L Ch R = 1 ,10575.4 ,98.1,96.7,95.4
XS GIS Cut Line= 3
     1653488.558       321683.11     1653863.558      321863.665
     1654028.489      322235.193
#Sta/Elev= 30
       0  881.85   154.9  843.94   183.9  838.79   222.6  833.96     271  825.81
   280.7  824.58     300   823.2   329.1  822.92   377.5  818.53   387.2  818.16
   416.2  818.63   435.6  817.51     484  813.59   551.7  810.34   571.1  808.13
   580.7  807.85   590.4  808.76   600.1  811.61   619.4   819.7   629.1  821.64
   638.8  825.36   648.5  831.95   658.2  839.64   696.9  872.74   706.6  880.64
   716.2  886.48   764.6  908.13     784  915.87   803.3   921.9   822.7  926.56
#Mann= 3 , 0 , 0
       0     .06       0   571.1    .045       0   590.4      .1       0
Bank Sta=571.1,590.4
XS Rating Curve= 0 ,0
Exp/Cntr=0.3,0.1

Type RM Length L Ch R = 1 ,10478.8 ,301.1,285.4,264.2
XS GIS Cut Line= 3
     1653471.197      321764.707       1653764.6      321903.596
      1653929.53       322223.04
#Sta/Elev= 30
       0  891.31    19.7  888.36    78.7  877.77   127.9  867.86   137.7  865.31
   157.4  858.96   177.1  851.49   216.4  839.52   245.9  828.89   255.8  826.46
   265.6  824.98   275.4  824.33   304.9  823.92   353.8   819.3   402.4  814.08
   460.6  810.88   480.1  808.94   489.8  808.04   499.5  808.11   505.7  809.09
   509.2  809.65   518.9   812.6   528.7  816.41   548.1  821.15   557.8  825.18
   616.1  862.75   645.3  880.24     655  884.93   664.7  888.32   684.1  893.34
#Mann= 3 , 0 , 0
       0     .06       0   480.1    .045       0   505.7      .1       0
Bank Sta=480.1,505.7
XS Rating Curve= 0 ,0
Exp/Cntr=0.3,0.1

Type RM Length L Ch R = 1 ,10193.3 ,258.5,261.2,269.3
XS GIS Cut Line= 3
     1653368.766      321950.471     1653740.748      322232.457
     1653940.401      322256.329
#Sta/Elev= 30
       0  924.15     9.7  921.45    19.4  916.89    29.2  910.78    58.4   891.2
     107  856.25   116.7  849.84   126.4  845.04     175  823.48   204.2  812.46
   213.9  809.58   223.7  807.67   245.6  805.95   262.6   805.8   272.3   805.8
   311.2  807.67   320.9   806.6   330.6  806.46   369.5  815.28   379.3  816.85
     389  817.66   408.4  818.17   447.3  818.18   457.1  819.22   466.8  821.03
   485.9  827.15   514.7   838.1     620  882.66   639.1  889.66   667.9  898.81
#Mann= 3 , 0 , 0
       0      .1       0   245.6    .045       0   272.3     .06       0
Bank Sta=245.6,272.3
XS Rating Curve= 0 ,0
Exp/Cntr=0.3,0.1

Type RM Length L Ch R = 1 ,9932.1  ,258.2,255.8,253.4
XS GIS Cut Line= 2
      1653170.85      322141.443     1653754.183      322479.985
#Sta/Elev= 30
       0  919.67    48.9  919.01    58.6  918.51    68.4  916.63    78.2  912.06
      88  905.76   117.3   884.3   156.4  854.67   166.2  847.99   175.9  842.62
   234.6   811.9   244.4  807.36   250.2  806.55   254.1  806.01   263.9   805.8
   273.7  805.94   283.5  806.64   322.6  810.86   381.2  815.55   439.9  818.92
   498.5  823.51   508.3  823.94   527.8  823.68   547.4  822.36   566.9  820.47
   576.7  820.51   596.3   822.6   615.8  823.85   645.1  826.41   674.4   828.2
#Mann= 3 , 0 , 0
       0      .1       0   250.2    .045       0   273.7     .06       0
Bank Sta=250.2,273.7
XS Rating Curve= 0 ,0
Exp/Cntr=0.3,0.1

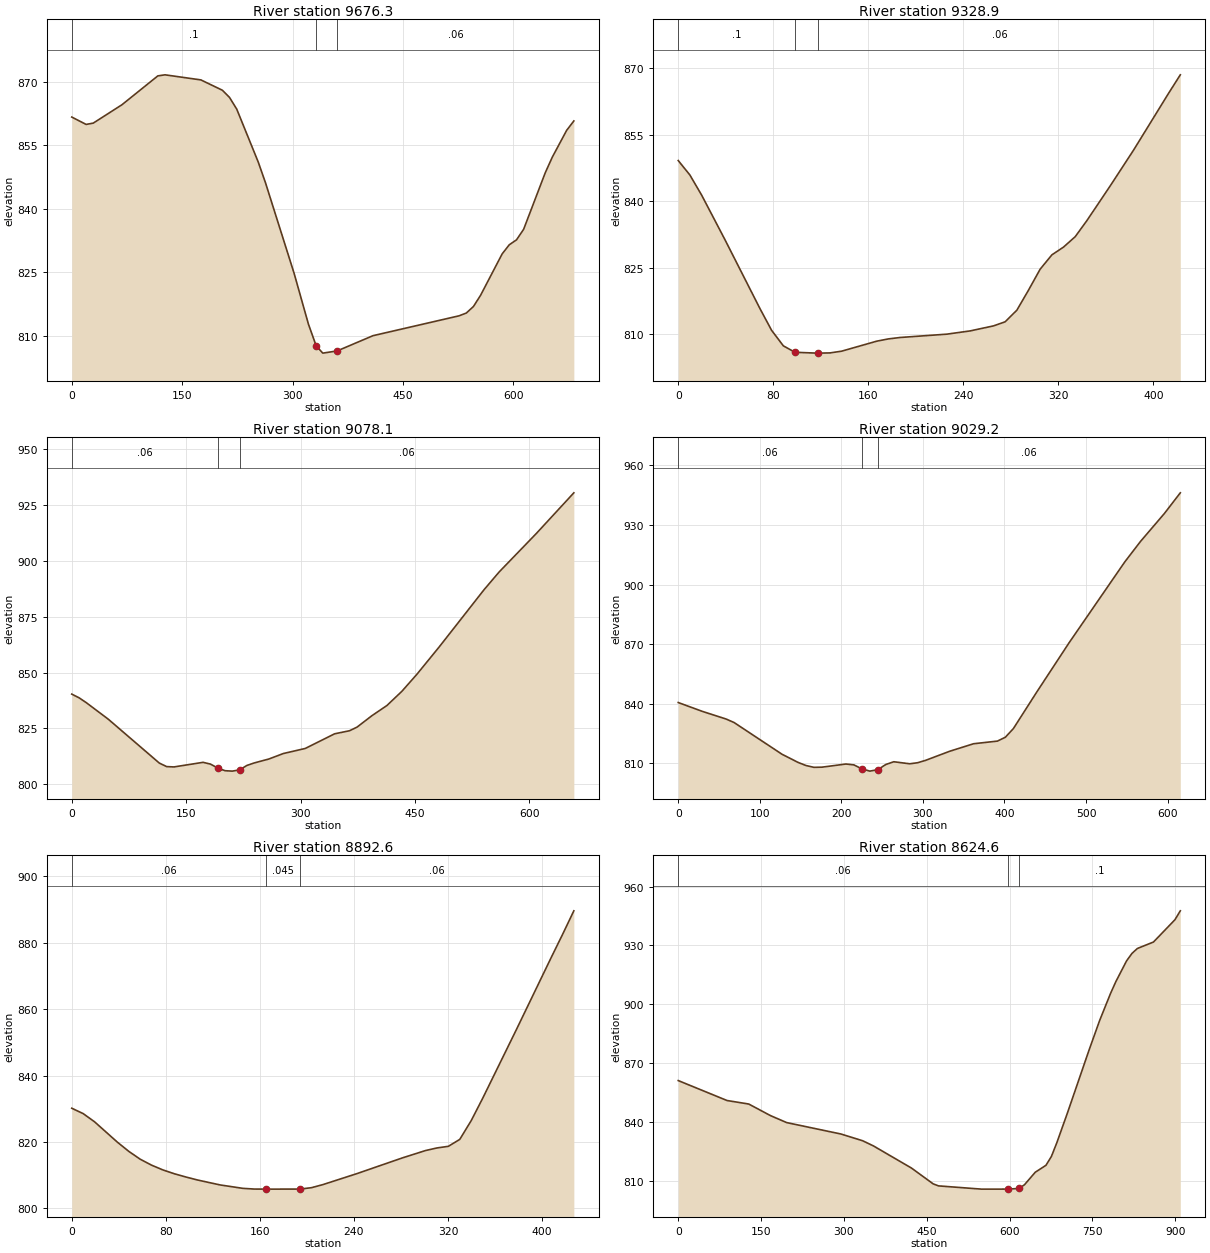
Type RM Length L Ch R = 1 ,9676.3  ,347.5,347.4,347.3
XS GIS Cut Line= 2
     1652957.362      322355.063     1653580.337       322632.61
#Sta/Elev= 30
       0  861.62    19.5  859.88    29.2  860.19    68.2  864.53   116.9  871.34
   126.7  871.59   175.4  870.39   204.6  867.95   214.3  866.25   224.1  863.49
   253.3     851   263.1  846.13     302  824.74   321.5  812.72   332.1  807.57
     341  805.89   360.5  806.41   409.2  810.01   526.1   814.7   535.9  815.35
   545.6  816.89   555.4  819.57   584.6  829.31   594.3  831.47   604.1  832.63
   613.8  835.12     643   848.4   652.8  852.18   672.3   858.5     682   860.7
#Mann= 3 , 0 , 0
       0      .1       0   332.1    .045       0   360.5     .06       0
Bank Sta=332.1,360.5
XS Rating Curve= 0 ,0
Exp/Cntr=0.3,0.1

Type RM Length L Ch R = 1 ,9328.9  ,237.4,250.8,264.1
XS GIS Cut Line= 2
     1653049.569      322776.036     1653440.194      322937.494
#Sta/Elev= 30
       0  849.16     9.8  845.91    19.7  841.38    39.3  831.36    68.8  815.83
    78.6  810.94    88.5  807.44    98.3  805.99   116.7   805.8     118   805.8
   127.8  805.85   137.6  806.24   167.1  808.49   176.9     809   186.8  809.32
   226.1  810.07   245.7   810.8   265.4  811.93   275.2  812.85   285.1  815.47
   294.9  819.98   304.7   824.7   314.6  827.93   324.4  829.68   334.2  832.01
     344  835.62   363.7  843.46   383.4  851.53   412.8  864.29   422.7  868.46
#Mann= 3 , 0 , 0
       0      .1       0    98.3    .045       0     118     .06       0
Bank Sta=98.3,118
XS Rating Curve= 0 ,0
Exp/Cntr=0.3,0.1

Type RM Length L Ch R = 1 ,9078.1  ,49.2,48.8,48.5
XS GIS Cut Line= 3
     1652973.537      322867.585     1653158.697      323146.651
     1653456.176      323273.835
#Sta/Elev= 30
       0  840.32     9.6  838.67    19.1  836.48    47.8  829.11   114.8  809.43
   124.4  807.85     134   807.7   172.2  809.76   181.8  808.98   191.4  807.24
   200.9  806.01   210.5  805.82   220.1  806.38   229.6  808.36   239.2  809.48
   258.4  811.24   277.5  813.71   306.2  815.98   344.7  822.54   364.3  823.92
   374.1  825.54   393.7  830.68   413.3  835.22   432.9  841.58   452.6  849.21
     482  861.53   540.8  887.16   560.4  895.02   609.4  912.35   658.4   930.5
#Mann= 3 , 0 , 0
       0     .06       0   191.4    .045       0   220.1     .06       0
Bank Sta=191.4,220.1
XS Rating Curve= 0 ,0
Exp/Cntr=0.3,0.1

Type RM Length L Ch R = 1 ,9029.2  ,133.5,136.7,139.7
XS GIS Cut Line= 3
     1652911.037      322867.585     1653115.898      323166.196
      1653119.37      323419.668
#Sta/Elev= 30
       0  840.51    29.4  836.08    58.7   832.2    68.5  830.43   127.2  814.46
   146.8  810.36   156.6  808.77   166.4  807.85   176.2  807.93   205.5  809.52
   215.3   809.1   225.1   807.1   234.9  805.94   244.7  806.68   254.5  809.28
   264.3  810.67   283.8  809.64   293.6  810.18   303.4  811.39   332.8  815.95
   362.1  819.74   391.4  821.08   401.1  823.03   410.9  827.37   440.1  846.13
   479.1  870.56   547.4  911.33   566.9  921.77   596.1  935.81   615.6  946.22
#Mann= 3 , 0 , 0
       0     .06       0   225.1    .045       0   244.7     .06       0
Bank Sta=225.1,244.7
XS Rating Curve= 0 ,0
Exp/Cntr=0.3,0.1

Type RM Length L Ch R = 1 ,8892.6  ,254.3,267.9,281.6
XS GIS Cut Line= 2
     1652848.769      322975.161     1653044.082      323354.935
#Sta/Elev= 30
       0  830.16     9.7  828.54    19.4  826.07    38.8  819.94    48.5  817.17
    58.2  814.81    67.9  813.01    77.6  811.57    87.4  810.41    97.1  809.45
   106.8  808.56   126.2  807.06   145.6  806.03   155.3  805.82     165   805.8
   194.1  805.81   203.8  806.23   213.5  807.15   242.6  810.48   281.5  815.24
   300.9  817.42   310.6   818.2   320.3  818.69     330  820.78   339.7  826.42
   349.4   833.1   378.5   854.1   407.6  875.43   417.4  882.49     427   889.6
#Mann= 3 , 0 , 0
       0     .06       0     165    .045       0   194.1     .06       0
Bank Sta=165,194.1
XS Rating Curve= 0 ,0
Exp/Cntr=0.3,0.1

Type RM Length L Ch R = 1 ,8624.6  ,370.2,401.3,432.3
XS GIS Cut Line= 3
     1652977.141      322695.744     1652742.766      323082.029
     1652703.703      323537.758
#Sta/Elev= 30
       0  861.13    88.4  850.96   127.7  849.17     167  843.28   196.4  839.71
   294.7  833.89     334  830.45   353.6  827.81   422.4  816.53   461.6   808.5
   471.3  807.45   549.2   805.8   597.8  805.81   617.3  806.16     627  808.03
   646.5   814.4   665.9  817.94   675.7  822.42   685.4   829.3   704.9   844.7
   743.8  876.55   763.2   891.8   782.7  905.43   792.4  911.52   811.9  922.14
   821.6  925.91   831.4  928.44   860.6  931.74   899.5  943.11   909.2  947.64
#Mann= 3 , 0 , 0
       0     .06       0   597.8    .045       0   617.3      .1       0
Bank Sta=597.8,617.3
XS Rating Curve= 0 ,0
Exp/Cntr=0.3,0.1

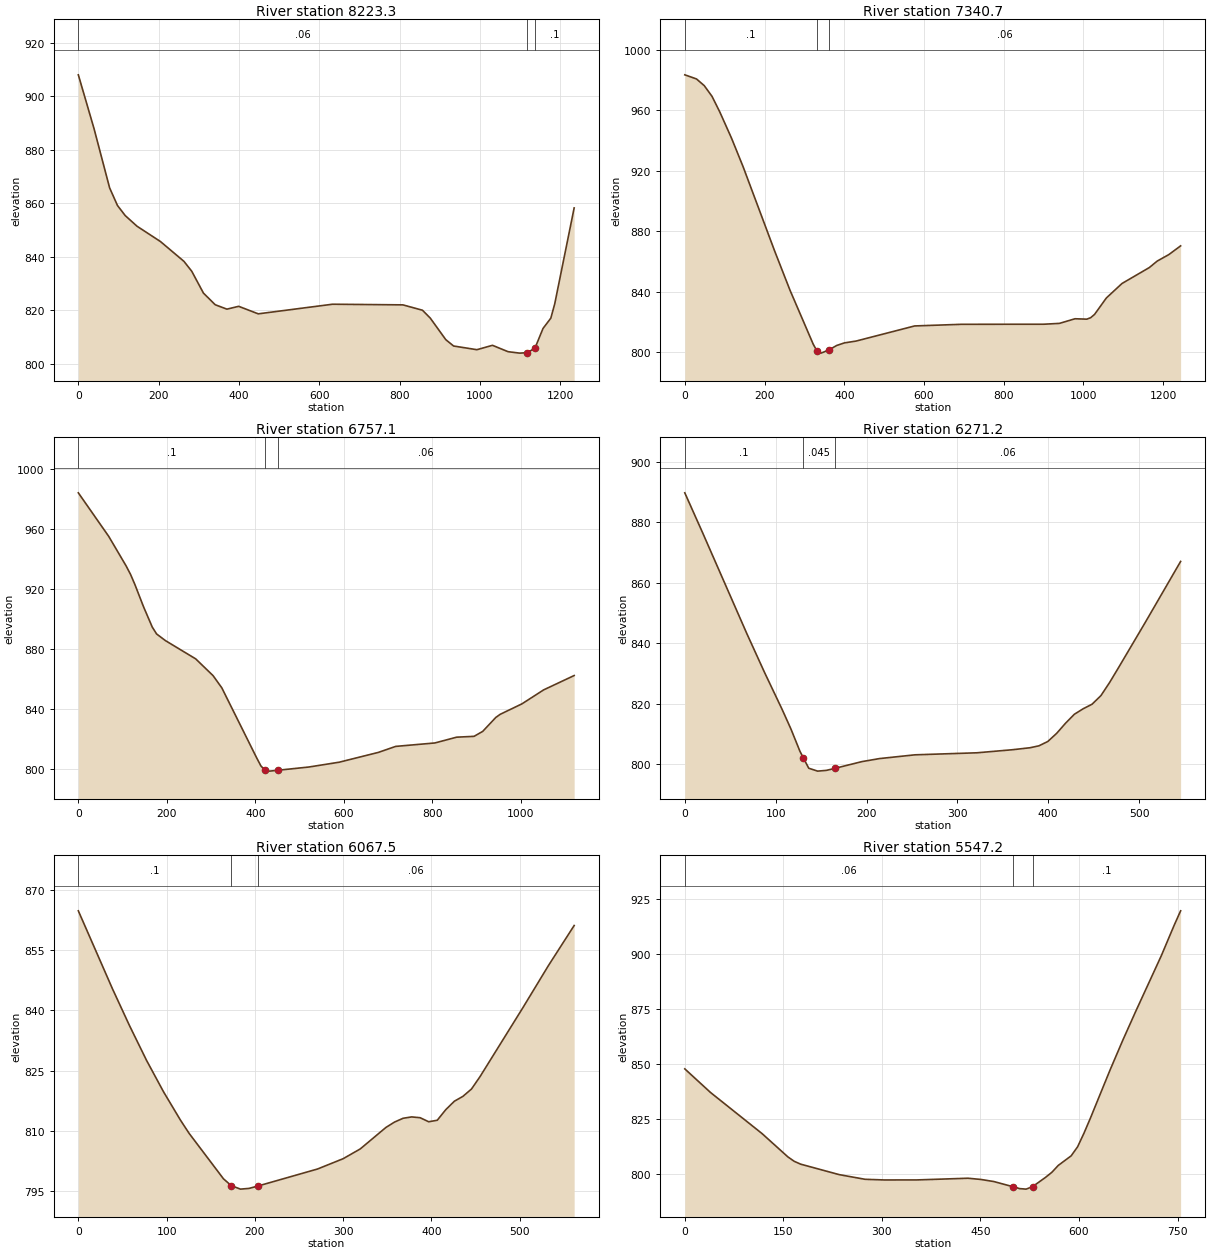
Type RM Length L Ch R = 1 ,8223.3  ,906.2,882.7,858.8
XS GIS Cut Line= 3
     1652856.378      322138.165       1652705.5      322981.577
     1652330.337      323025.318
#Sta/Elev= 30
       0     908      39  887.96    77.9  865.79    97.4  859.23   116.8  855.43
     146  851.48   204.5  845.75   262.9  838.36   282.4  834.65   311.6  826.48
   340.8  822.15     370   820.5   399.2  821.56   447.9  818.75   632.9  822.34
   808.1   822.1   856.8   820.1   876.2  817.17   914.9  809.11   934.3  806.74
   992.4  805.36  1031.1     807  1069.9  804.62  1098.9  804.08  1118.3  804.25
  1137.1     806    1157   813.3  1176.4  817.13  1186.1  822.46  1234.5   858.3
#Mann= 3 , 0 , 0
       0     .06       0  1118.3    .045       0  1137.1      .1       0
Bank Sta=1118.3,1137.1
XS Rating Curve= 0 ,0
Exp/Cntr=0.3,0.1

Type RM Length L Ch R = 1 ,7340.7  ,616.1,583.6,551.1
XS GIS Cut Line= 4
     1652794.982      321891.009     1652554.096      322338.058
     1652406.527      322546.391     1652308.738      323016.925
#Sta/Elev= 30
       0  983.44    29.3  980.72    48.8  976.29    68.4  969.15    87.9  958.82
   117.2  941.56   146.5  922.51   224.6  867.47   263.7  841.11   322.3   805.2
     332   800.6   341.8  799.39   361.3  801.47   380.9  804.44   400.4  806.16
   429.7  807.37   576.6  817.37   694.4  818.45   900.4   818.5   939.7  819.06
   978.9  822.12  1008.3  821.85  1018.1  822.82  1027.9  825.02  1057.4  835.86
  1096.6  845.43  1165.2  855.98  1184.9  860.25  1214.3  864.59  1243.7  870.32
#Mann= 3 , 0 , 0
       0      .1       0     332    .045       0   361.3     .06       0
Bank Sta=332,361.3
XS Rating Curve= 0 ,0
Exp/Cntr=0.3,0.1

Type RM Length L Ch R = 1 ,6757.1  ,488.6,485.9,483.2
XS GIS Cut Line= 3
     1651792.378      322186.148     1652371.805      322609.325
     1652289.339       323004.29
#Sta/Elev= 30
       0   984.3    68.8  955.24   108.1  935.55     118  929.97   127.8  923.24
   147.4  908.37   167.1  894.86   176.9  890.25   196.6  885.86   265.4  873.62
   304.7  862.43   324.4  854.32     403  807.76   412.8  802.27   422.6  799.24
   432.5  798.81   450.7  799.37   520.9  801.54   589.7  804.75   678.2  811.28
   717.5  815.29   806.1  817.58   855.3  821.44   894.6  821.99   914.3   825.3
   943.8  834.57   953.7  836.66  1002.9  843.64  1052.1  852.97    1121  862.52
#Mann= 3 , 0 , 0
       0      .1       0   422.6    .045       0   450.7     .06       0
Bank Sta=422.6,450.7
XS Rating Curve= 0 ,0
Exp/Cntr=0.3,0.1

Type RM Length L Ch R = 1 ,6271.2  ,203.6,203.6,203.7
XS GIS Cut Line= 2
     1651787.037      322797.654     1652262.731      323065.015
#Sta/Elev= 30
       0  889.66    19.5  876.54    68.2  843.18    87.7  830.33   107.2  818.02
   116.9  811.54   126.7  804.25   130.6  801.99   136.4  798.63   146.2  797.67
   155.9  797.92   165.6  798.62   194.9  800.81   214.4  801.82   253.4  803.06
   321.6  803.73   360.5  804.74     380   805.4   389.8  806.04   399.5  807.46
   409.3  810.17     419  813.49   428.8  816.48   438.5  818.29   448.2  819.78
     458  822.63   467.7  827.04   477.5  831.94   506.7  846.78   545.7  866.98
#Mann= 3 , 0 , 0
       0      .1       0   130.6    .045       0   165.6     .06       0
Bank Sta=130.6,165.6
XS Rating Curve= 0 ,0
Exp/Cntr=0.3,0.1

Type RM Length L Ch R = 1 ,6067.5  ,512.2,520.4,528.5
XS GIS Cut Line= 3
     1651716.878      322936.972     1651798.476      323032.459
     1652178.684         323246.
#Sta/Elev= 30
       0  864.72    38.6  845.38      58  836.19    77.3  827.56    96.6  819.73
   115.9  812.65   125.6  809.41   164.4  798.15   173.3  796.44   183.7  795.58
   193.4  795.76   203.1  796.33     271  800.58     300  803.14   319.4  805.57
   348.5  810.91   358.2  812.24   367.9  813.18   377.6  813.52   387.2  813.32
   396.9  812.32   406.6  812.69   416.3  815.33     426  817.42   435.7  818.63
   445.4  820.45   455.1  823.54   503.5  840.61   532.6  851.13   561.7  861.07
#Mann= 3 , 0 , 0
       0      .1       0   173.3    .045       0   203.1     .06       0
Bank Sta=173.3,203.1
XS Rating Curve= 0 ,0
Exp/Cntr=0.3,0.1

Type RM Length L Ch R = 1 ,5547.2  ,504.8,496.1,486.1
XS GIS Cut Line= 2
     1651373.739      323157.262     1651859.953       323734.46
#Sta/Elev= 30
       0  847.81    39.2  837.09   117.6  818.46   156.8  807.92   166.6  805.88
   176.4  804.59   235.2  799.83   274.4  797.73   303.8  797.43   352.8  797.44
   431.2  798.21   450.9  797.65   470.5   796.7   499.9  794.33   509.7   793.5
   519.5  793.27   529.3  794.39   548.9  798.56   558.7   800.9   568.5  804.03
   588.1  808.37   597.9  812.47   607.7  818.71   617.5  825.54   646.9  847.02
   666.5  860.68   686.1  873.72   725.3  899.12   744.9  912.96   754.7  919.49
#Mann= 3 , 0 , 0
       0     .06       0   499.9    .045       0   529.3      .1       0
Bank Sta=499.9,529.3
XS Rating Curve= 0 ,0
Exp/Cntr=0.3,0.1

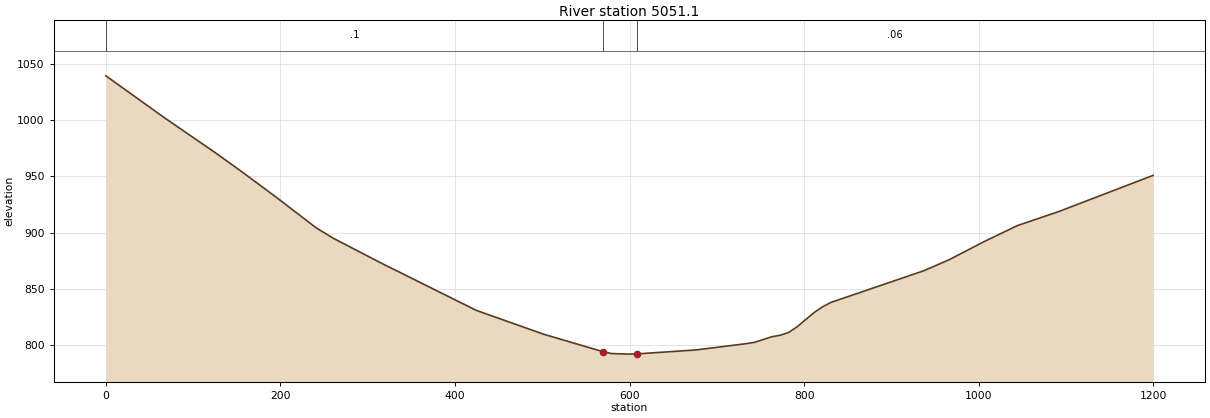
Type RM Length L Ch R = 1 ,5051.1  ,573.4,553.8,535.4
XS GIS Cut Line= 4
     1650674.756      323590.228     1651117.464       323618.44
      1651462.57      323813.397     1651819.341      323857.667
#Sta/Elev= 30
       0 1039.09    67.5 1001.67   125.4  970.86   154.3  954.81   192.9  932.68
   241.1  904.12   260.4  895.02   318.2  871.85   424.3  831.02   501.6  809.83
   569.3  794.42     579  792.75   598.3  792.21     608  792.39   675.6   795.9
   733.6  801.51   743.3  802.74   762.6   807.6   772.3  808.93     782   811.4
   791.6  816.35     811  828.97   820.6  834.01   830.3  838.02   937.1  866.24
   966.3  876.08  1005.2  891.73    1044   906.2  1092.6     919  1199.5  950.77
#Mann= 3 , 0 , 0
       0      .1       0   569.3    .045       0     608     .06       0
Bank Sta=569.3,608
XS Rating Curve= 0 ,0
Exp/Cntr=0.3,0.1