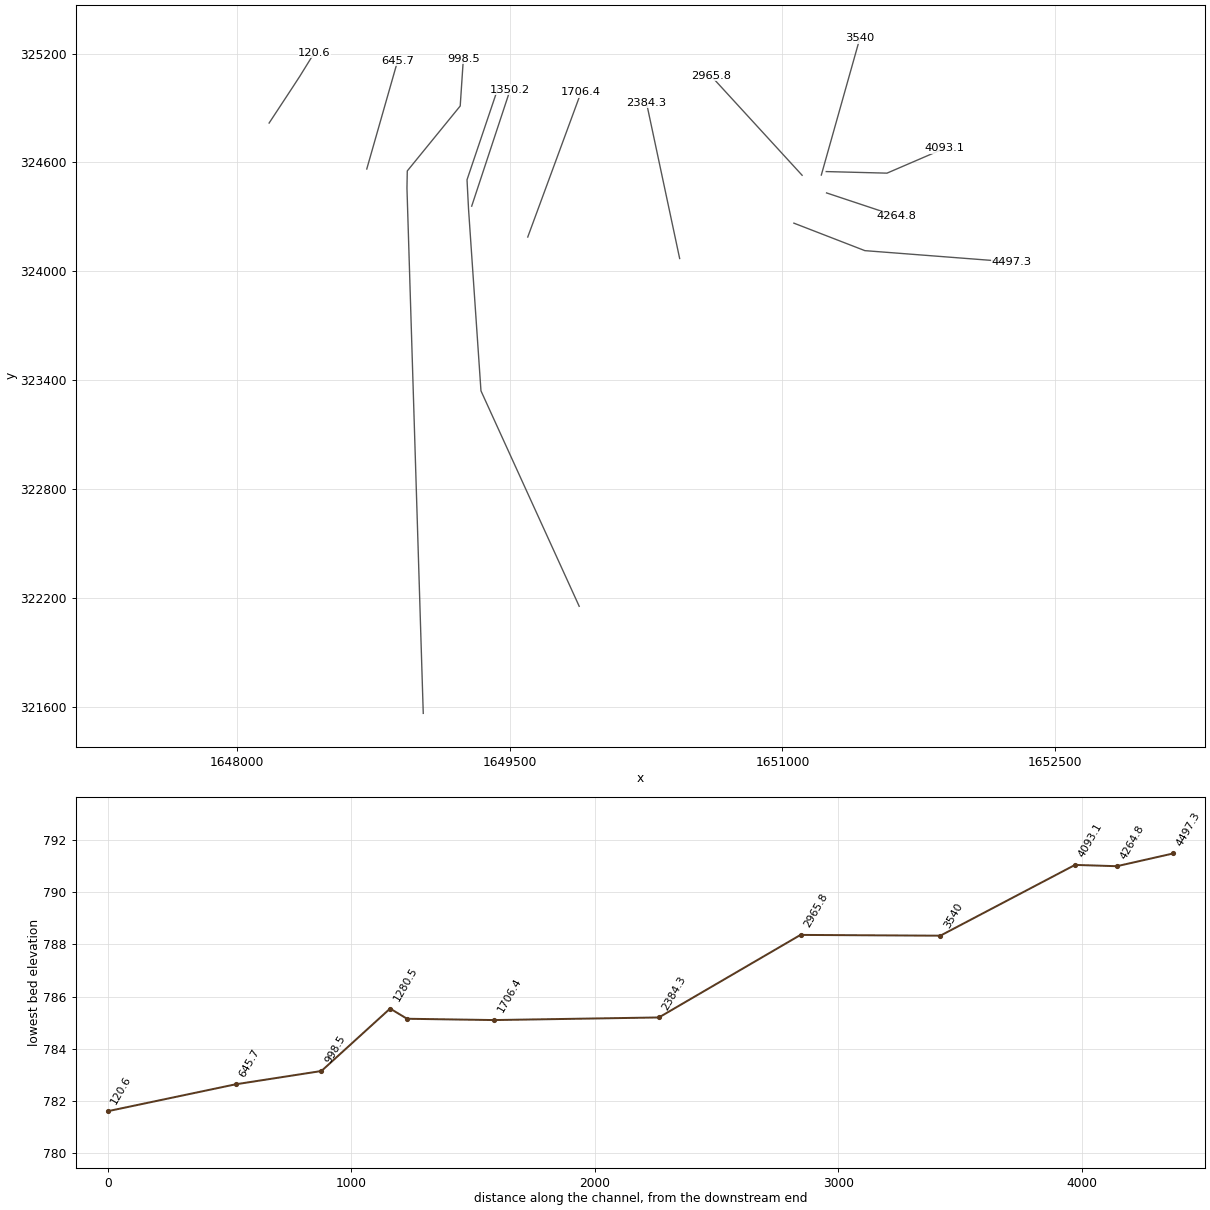
HEC-RAS study RBNSONFRK.prj: RBNSONFRK

--- RBNSONFRK.g01 (geometry) --- (continued)

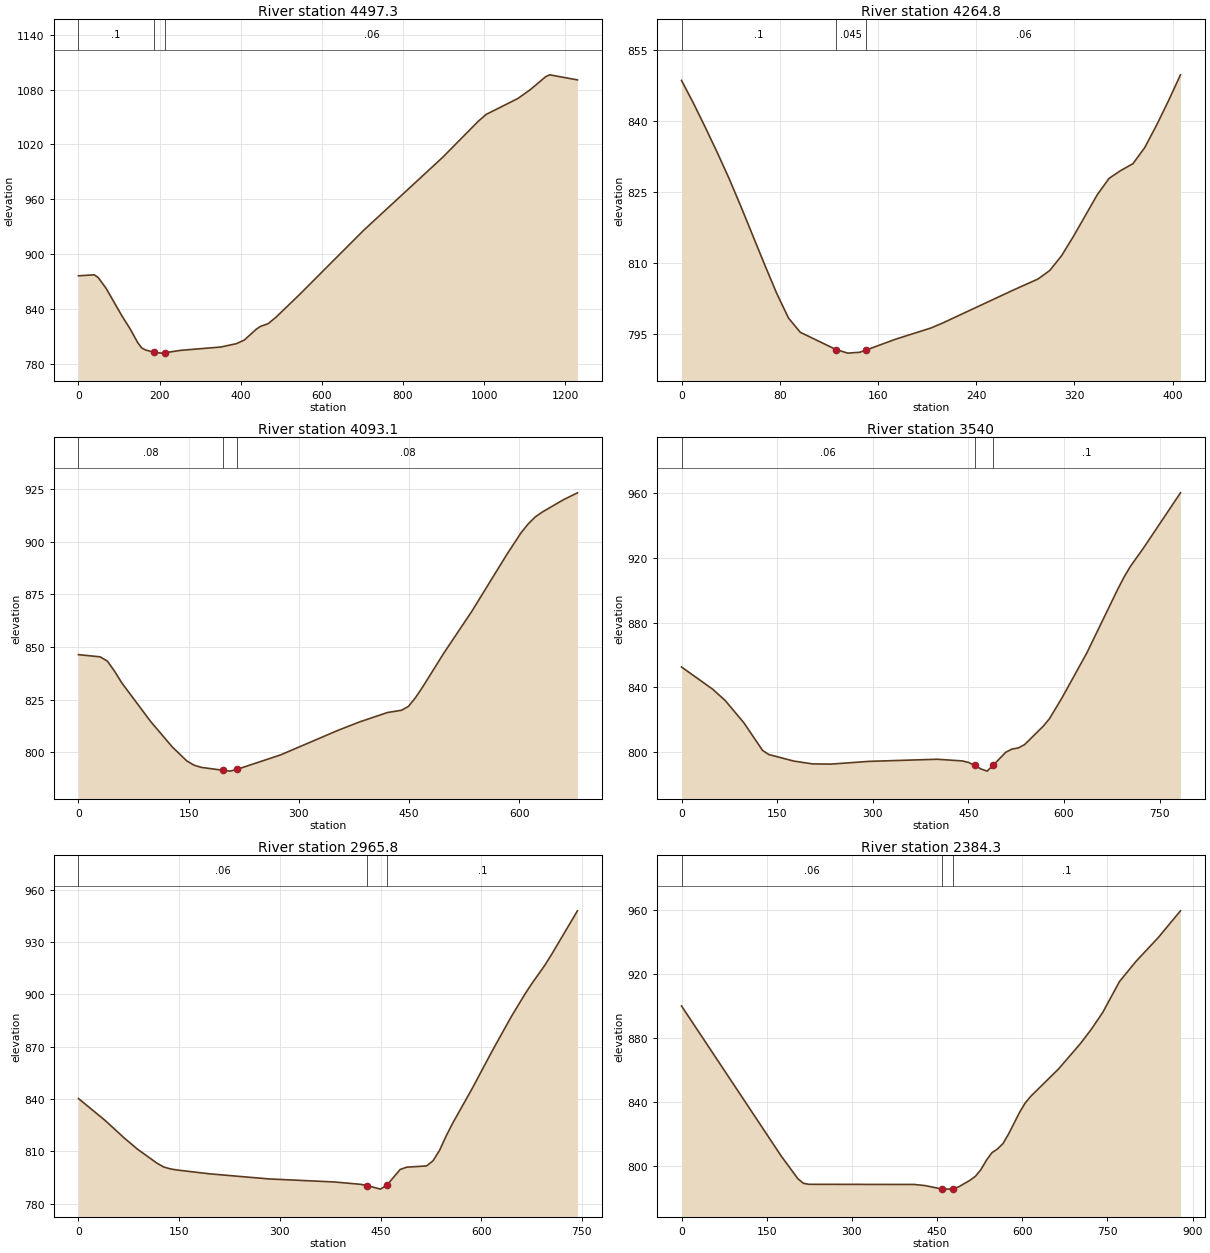
Type RM Length L Ch R = 1 ,4497.3  ,231.2,232.4,233.6
XS GIS Cut Line= 3
     1651063.211      324265.141     1651453.703      324113.626
     1652262.731      324051.126
#Sta/Elev= 30
       0  876.17      39  877.24    48.7  874.22    68.2   862.4   107.2   832.2
   126.6  818.64   146.1  802.98   155.8  797.21   165.6  794.91   185.1  792.54
   204.6  791.48   214.3     792   253.3  794.58   350.7  798.15   389.6  801.87
   409.1  805.88   438.4  817.69   448.2  820.66   467.7  823.73   487.3  830.94
     546  856.06   702.4  925.68   897.9 1005.88   985.9 1045.46  1005.4 1052.94
  1083.6 1070.41    1113 1079.67  1152.1 1094.24  1161.9 1096.27  1230.3 1090.71
#Mann= 3 , 0 , 0
       0      .1       0   185.1    .045       0   214.3     .06       0
Bank Sta=185.1,214.3
XS Rating Curve= 0 ,0
Exp/Cntr=0.3,0.1

Type RM Length L Ch R = 1 ,4264.8  ,165.1,171.7,178.8
XS GIS Cut Line= 2
      1651242.92      324431.764     1651628.337      324303.292
#Sta/Elev= 30
       0  848.54     9.7  843.74    19.4  838.62      29  833.39    38.7  827.86
    48.4  821.92    67.7  809.66    77.4  803.67    87.1   798.4    96.7  795.39
   125.8  791.75   135.4  790.99   145.1  791.17   150.6  791.66   174.1  793.91
   203.1  796.29   212.8  797.36   270.8  804.37   290.2  806.62   299.9  808.44
   309.5  811.55   319.2  815.65   338.6  824.44   348.2  827.88   357.9  829.56
   367.6  830.97   377.2  834.36   386.9  839.12   396.6  844.27   406.3  849.72
#Mann= 3 , 0 , 0
       0      .1       0   125.8    .045       0   150.6     .06       0
Bank Sta=125.8,150.6
XS Rating Curve= 0 ,0
Exp/Cntr=0.3,0.1

Type RM Length L Ch R = 1 ,4093.1  ,522.7,553.1,582.9
XS GIS Cut Line= 3
     1651241.162      324549.429     1651575.364      324540.749
     1651892.204      324677.467
#Sta/Elev= 30
       0  846.41    29.5  845.36    39.3  843.36    49.2  838.49      59  832.98
    98.3  814.61   127.8  802.51   147.5  795.89   157.3  793.88   167.2  792.82
   196.7  791.45   206.5  791.04   216.3  791.93   275.3  798.77   353.5  810.44
   382.2  814.36   420.6  818.89   439.8  819.97   449.3   821.8   458.9  825.98
   468.5  830.95   497.3  847.04   535.6  867.01   583.5  894.15   602.7  904.36
   612.3  908.52   621.9  911.85   631.5  914.18   660.2  920.01   679.4  923.32
#Mann= 3 , 0 , 0
       0     .08       0   196.7    .045       0   216.3     .08       0
Bank Sta=196.7,216.3
XS Rating Curve= 0 ,0
Exp/Cntr=0.3,0.1

Type RM Length L Ch R = 1 ,3540    ,551.2,574.2,597.1
XS GIS Cut Line= 2
      1651214.12      324530.293     1651425.926      325283.765
#Sta/Elev= 30
       0  852.68    48.9  838.93    68.5  831.98    97.8   818.2   127.2   801.1
     137  798.58   176.1  794.54   205.4   792.8   234.8  792.67   293.5  794.35
   401.1  795.67   440.3  794.64     450  793.74   459.8  791.94   469.6  789.69
   479.4  788.33   489.2  792.13   508.7     800   518.5  801.98   528.3  802.65
   538.1  804.69   567.4  816.08   577.2  820.72   596.8  833.57   635.9  861.42
   684.8   901.1   694.6  908.47   704.4  914.96     724  925.77   782.7  960.27
#Mann= 3 , 0 , 0
       0     .06       0   459.8    .045       0   489.2      .1       0
Bank Sta=459.8,489.2
XS Rating Curve= 0 ,0
Exp/Cntr=0.3,0.1

Type RM Length L Ch R = 1 ,2965.8  ,593.5,581.5,569.5
XS GIS Cut Line= 2
     1651108.545      324528.986     1650606.809      325077.597
#Sta/Elev= 30
       0   840.3    39.1  827.96    68.5  817.57      88  811.25   117.4  803.12
   127.2  801.03     137  799.96   146.7  799.34   195.6  797.12   283.7  794.21
   381.5  792.46   420.6   791.1   430.4  790.38     450  788.36   459.8   790.8
   479.3  799.63   489.1  800.96   518.5  801.65   528.2   804.6     538  810.61
   547.8  818.85   557.6  826.22   586.9  846.28   616.3  867.53   645.6  887.78
   665.2  900.21     675  905.99   694.5  916.56   704.3  922.56   743.4  947.96
#Mann= 3 , 0 , 0
       0     .06       0   430.4    .045       0   459.8      .1       0
Bank Sta=430.4,459.8
XS Rating Curve= 0 ,0
Exp/Cntr=0.3,0.1

Type RM Length L Ch R = 1 ,2384.3  ,690.8,677.9,665.1
XS GIS Cut Line= 2
     1650434.985      324070.306     1650252.314      324929.598
#Sta/Elev= 30
       0  900.04   175.7  805.86     205  791.68   214.7  788.84   224.5  788.22
     410  788.12   429.5  787.39   458.8  785.22   468.5   785.2   478.3  785.41
     488  786.64   507.6  790.69   517.3  793.17   527.1  797.39   536.9  803.37
   546.6  808.04   556.4  810.38   566.1  813.81   575.9  819.78   595.4  833.46
   605.2  839.22     615  843.42   663.8  860.53   702.8  876.64   722.3  885.79
   741.8  896.07   771.1  915.32   800.4  928.05   839.4   942.9   878.5  959.66
#Mann= 3 , 0 , 0
       0     .06       0   458.8    .045       0   478.3      .1       0
Bank Sta=458.8,478.3
XS Rating Curve= 0 ,0
Exp/Cntr=0.3,0.1

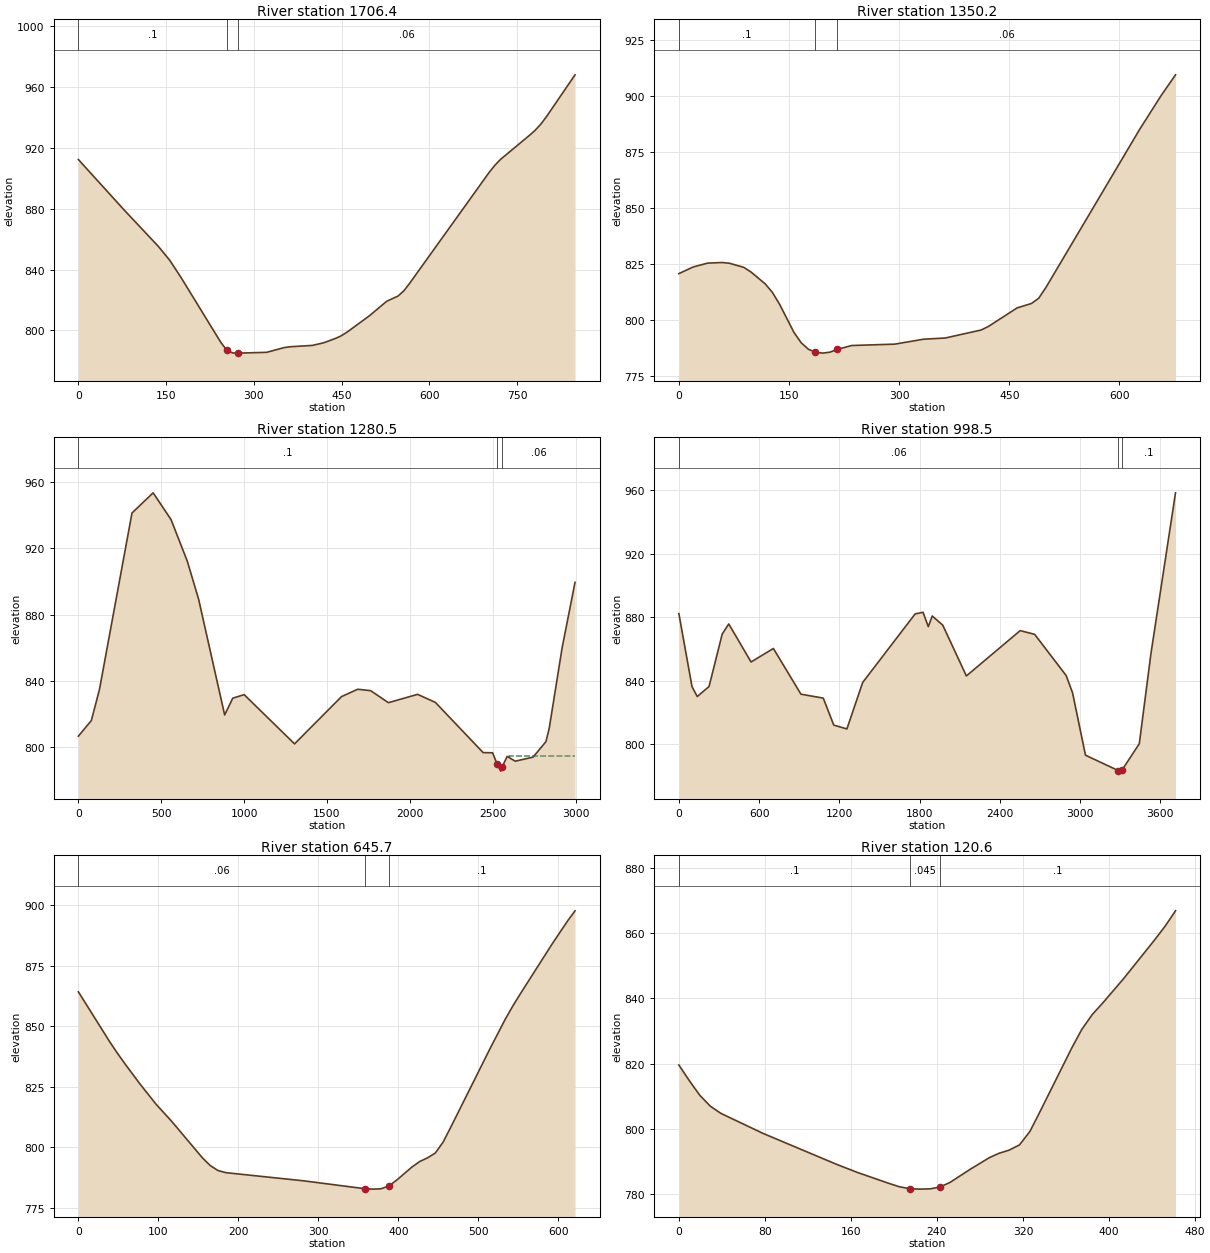
Type RM Length L Ch R = 1 ,1706.4  ,355.5,356.3,356.9
XS GIS Cut Line= 2
     1649599.537      324188.626     1649892.258      324985.272
#Sta/Elev= 30
       0  912.42      78  879.32   136.6  855.32   156.1  846.19   175.6  834.73
   243.9  791.88   253.5  787.15   263.4  785.22   273.2   785.1   321.9  785.63
   351.2  788.69     361  789.26     400  790.18   419.5  791.93     439   794.7
   448.8  796.42   458.5  798.73   497.5   809.7   526.8  819.19   546.3  822.65
   556.1  826.02   565.8  830.86   702.4  904.17   712.2  908.82   721.9  912.67
   770.7  928.26   780.4  931.57   790.2  935.66     800  940.65   848.7  968.11
#Mann= 3 , 0 , 0
       0      .1       0   253.5    .045       0   273.2     .06       0
Bank Sta=253.5,273.2
XS Rating Curve= 0 ,0
Exp/Cntr=0.3,0.1

Type RM Length L Ch R = 1 ,1350.2  ,69.8,69.7,69.5
XS GIS Cut Line= 2
     1649291.245      324358.904     1649503.051      325001.266
#Sta/Elev= 30
       0  820.69    19.6  823.68    39.2   825.4    58.8  825.66    68.6  825.35
    88.2  823.53      98  821.48   117.6  816.11   127.4   812.3   137.2  806.98
   156.8  794.38   166.6  789.78   176.4  786.89   185.7  785.61     196  785.15
   205.8  785.59   215.7   786.8   235.3  788.55   294.1  789.17   333.3  791.38
   362.7   791.9   411.7  795.49   421.5  797.06   460.7  805.38   480.3  807.35
   490.1   809.7   499.9   814.5   627.4  885.11   656.8   900.3   676.4  909.58
#Mann= 3 , 0 , 0
       0      .1       0   185.7    .045       0   215.7     .06       0
Bank Sta=185.7,215.7
XS Rating Curve= 0 ,0
Exp/Cntr=0.3,0.1

Type RM Length L Ch R = 1 ,1280.5  ,290.3,282,273.8
XS GIS Cut Line= 5
      1649882.42      322153.501     1649342.228      323340.783
     1649273.714      324344.568     1649265.495      324504.135
     1649433.606      325003.002
#Sta/Elev= 30
       0  806.61    78.5   816.1   127.5   834.9   323.6  941.25   451.1  953.41
     559   937.3   657.1  912.23   725.8  889.14   882.7  819.42   931.7  829.55
  1000.4  831.67  1304.4  801.98  1587.7  830.48  1685.4  834.93  1763.5  834.08
    1871  826.82  2046.8  831.85  2154.2  826.99  2442.1  796.73  2499.5  796.59
  2525.8     790  2548.3  785.54    2558   788.3  2587.3  794.41    2636  791.54
  2743.3  793.98  2821.2  803.32  2840.8  811.22  2918.7  859.83  2996.7   899.4
#Mann= 3 , 0 , 0
       0      .1       0  2525.8    .045       0    2558     .06       0
#XS Ineff= 2 , 0
                         2596.67           794.6
Permanent Ineff=
       F       F
Bank Sta=2525.8,2558
XS Rating Curve= 0 ,0
Exp/Cntr=0.3,0.1

Type RM Length L Ch R = 1 ,998.5   ,343.9,352.8,361.6
XS GIS Cut Line= 5
     1649024.781      321563.223     1648935.173      324457.415
     1648936.909      324552.901     1649228.009      324910.848
      1649245.37      325171.265
#Sta/Elev= 30
       0  882.29    98.2  836.35   137.4   830.1   225.8  836.44   323.9  869.41
     373  875.79   539.8  851.85   706.7  860.35   912.8  831.58  1079.7   829.1
  1158.2  812.12  1256.4  809.71  1374.2  838.95  1766.8  882.13  1825.7  883.12
    1865  874.11  1894.4   880.8  1972.9  875.05  2149.6  843.07    2552  871.59
    2660  869.26  2895.6  843.33  2943.3  832.51  3040.2  793.18  3285.6  783.49
  3295.4  783.15    3315  784.03  3442.6   800.4  3529.8  857.22  3713.4  958.33
#Mann= 3 , 0 , 0
       0     .06       0  3285.6    .045       0    3315      .1       0
Bank Sta=3285.6,3315
XS Rating Curve= 0 ,0
Exp/Cntr=0.3,0.1

Type RM Length L Ch R = 1 ,645.7   ,532.1,525.1,518.2
XS GIS Cut Line= 2
      1648714.12      324563.626     1648884.259      325160.848
#Sta/Elev= 30
       0  864.16    38.8  843.72    48.5  838.94    58.2  834.43    77.6  825.85
      97  817.78   116.4  810.75   155.2  795.53     165  792.35   174.6  790.32
   184.4  789.44   281.4  786.08     359  782.78   368.7  782.64   378.4  782.77
   388.1  783.93   397.8   786.3   417.2   791.8   426.9  794.07   436.6  795.56
   446.3  797.56     456  802.03   465.7  808.26   514.2  840.34   533.7  852.81
   543.4   858.4   553.1  863.58   591.9  883.68   611.3  893.25     621  897.62
#Mann= 3 , 0 , 0
       0     .06       0     359    .045       0   388.1      .1       0
Bank Sta=359,388.1
XS Rating Curve= 0 ,0
Exp/Cntr=0.3,0.1

Type RM Length L Ch R = 1 ,120.6   ,112.6,120.6,128.5
XS GIS Cut Line= 4
     1648176.971      324816.851     1648300.244      325004.661
      1648345.19      325073.725     1648426.537      325205.306
#Sta/Elev= 30
       0  819.61     9.8  814.79    19.5  810.33    29.3  806.99    39.1   804.8
    78.1   798.7   146.5  789.22     166  786.72   195.4  783.36   205.1  782.33
   214.9  781.72   224.6  781.61   233.8   781.7   242.7  782.25   252.1  783.66
   270.4  787.58   288.7  791.25   297.9  792.61     307  793.54   316.7  795.15
   326.4  799.27   336.1  805.53   365.1  824.69   374.7  830.54   384.4  835.08
   394.1   838.6   413.4  846.01   442.4  857.94   452.1  862.12   461.8  866.83
#Mann= 3 , 0 , 0
       0      .1       0   214.9    .045       0   242.7      .1       0
Bank Sta=214.9,242.7
XS Rating Curve= 0 ,0
Exp/Cntr=0.3,0.1

Chan Stop Cuts=-1
Use User Specified Reach Order=0
Composite Channel Slope=5